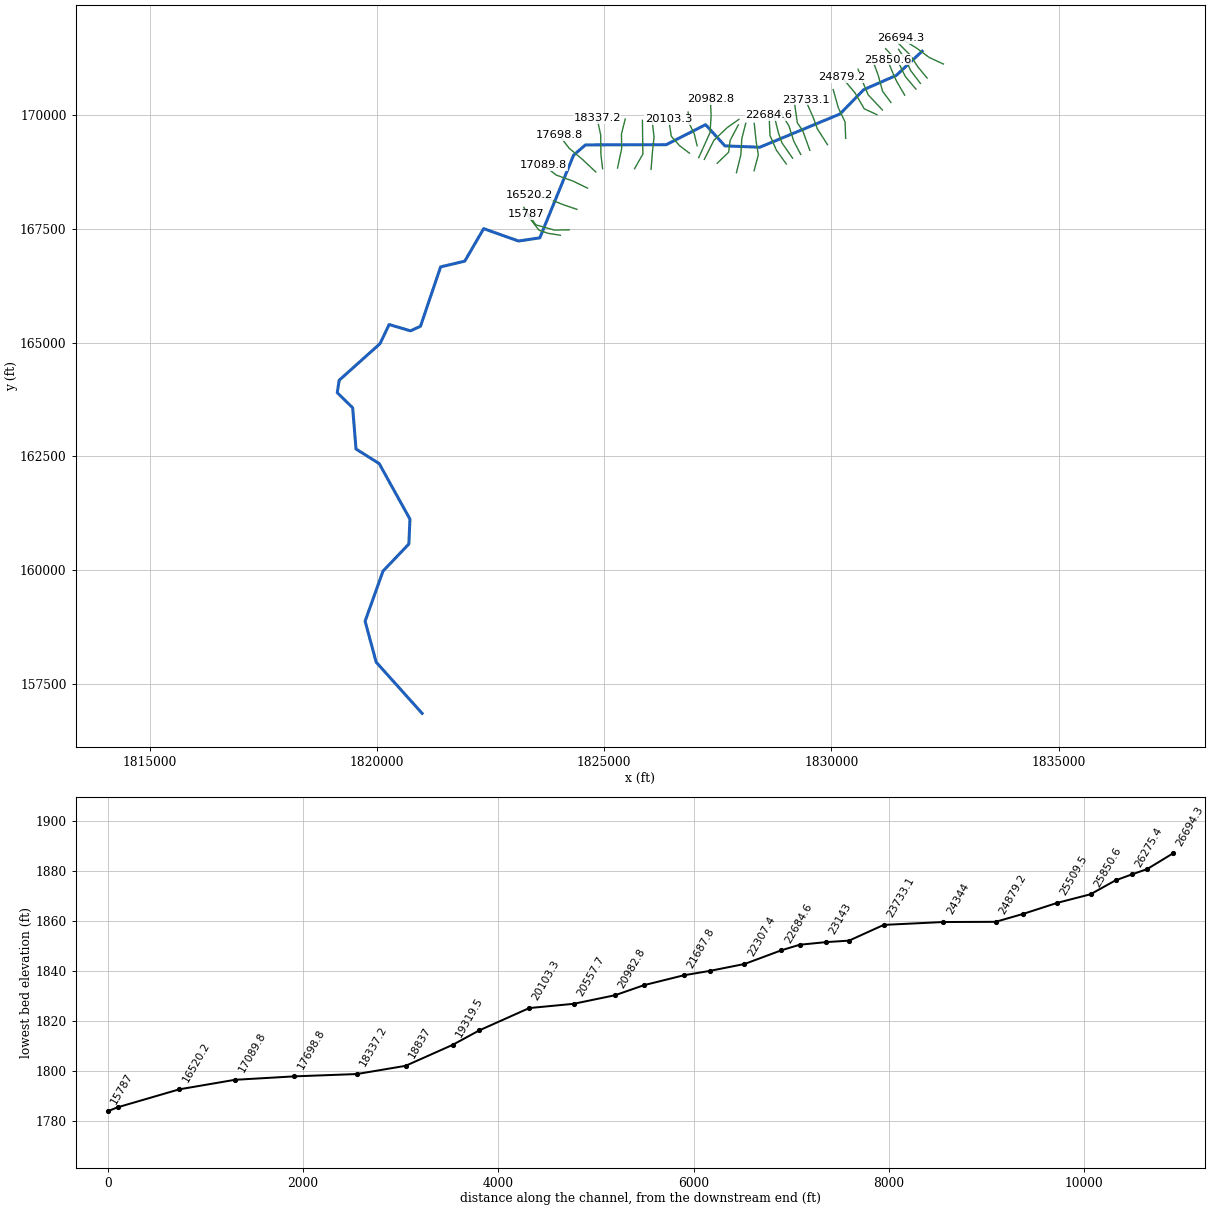
--- Laurel Branch B.prj (project) ---

Proj Title=Laurel Branch B
Current Plan=p01
Default Exp/Contr=0,0
English Units
Geom File=g01
Flow File=f01
Plan File=p01
BEGIN DESCRIPTION:
END DESCRIPTION:
DSS Export Rating Curves= 0
DSS Export Rating Curve Sorted= 0
DSS Export Volume Flow Curves= 0
DXF OffsetX= 0
DXF OffsetY= 0
DXF ScaleX= 0
DXF ScaleY= 0

--- Laurel Branch B.p01 (plan) ---

Plan Title=Floodplain
Program Version=4.00
Geom File=g01
Flow File=f01
K Sum by GR=0
Std Step Tol=0.01
Critical Tol=0.01
Num of Std Step Trials=20
Max Error Tol=0.3
Flow Tol Ratio=0.001
Split Flow NTrial=30
Split Flow Tol=0.02
Split Flow Ratio=0.02
Log Output Level=0
Friction Slope Method=1
Unsteady Friction Slope Method=2
Unsteady Bridges Friction Slope Method=1
Global Log Level=0
CheckData=False
Run HTab=0
Run UNet=0
Run PostProcess=0
UNET Theta=0
UNET Theta Warmup=0
UNET ZTol=0
UNET ZSATol=0
UNET MxIter=0
UNET MaxInSteps=0
UNET DtIC=0
UNET DtMin=0
UNET MaxCRTS=0
UNET WFStab=0
UNET SFStab=0
UNET WFX=0
UNET SFX=0
UNET DSS MLevel=0
UNET DZMax Abort=0
UNET Convert EG Bridges=0
UNET Use Existing IB Tables=0
UNET Froude Limit=0
UNET Froude Power=0
Write IC File=0
Echo Input=False
Echo Output=False
Write Detailed=0

--- Laurel Branch B.f01 (steady flow) ---

Flow Title=NFF Regression Equation
Program Version=4.00
Number of Profiles=1
Profile Names=P100yr
River Rch & RM=Laurel Branch B,Main      ,26694.3
715.4460
River Rch & RM=Laurel Branch B,Main      ,25160.5
764.9181
River Rch & RM=Laurel Branch B,Main      ,23378
841.6601
River Rch & RM=Laurel Branch B,Main      ,21277.9
933.2551
River Rch & RM=Laurel Branch B,Main      ,20982.8
1089.190
River Rch & RM=Laurel Branch B,Main      ,15887.1
1182.133
River Rch & RM=Laurel Branch B,Main      ,15586.9
1456.347
River Rch & RM=Laurel Branch B,Main      ,14373.7
1483.979
River Rch & RM=Laurel Branch B,Main      ,14078.6
1779.470
River Rch & RM=Laurel Branch B,Main      ,6095.1
1963.958
River Rch & RM=Laurel Branch B,Main      ,291.1
2178.613
Boundary for River Rch & Prof#=Laurel Branch B,Main      ,1
Up Type=0
Dn Type=3
Dn Slope=0.000001

--- Laurel Branch B.g01 (geometry) ---

Geom Title=USGS 10m DEM
Program Version=4.00

River Reach=Laurel Branch B ,Main
Reach XY= 30
     1831996.068      171411.157     1831426.987      170878.224
     1830710.539      170564.951     1830185.948      170028.311
     1828423.648      169298.618     1827655.556      169327.735
      1827229.72      169795.052     1826361.414      169353.524
      1824585.86      169349.979     1824324.491      169124.061
     1823580.875      167304.945     1823112.183      167235.392
      1822345.17      167507.501     1821929.766      166792.594
     1821397.991      166666.775     1820954.497      165360.624
     1820735.531      165259.831     1820264.928      165398.857
     1820064.035      164977.607     1819165.231      164173.341
     1819122.829       163899.46     1819462.052      163567.883
     1819535.736      162660.737     1820045.267      162340.977
     1820723.019      161118.242     1820698.608      160571.557
     1820128.682      159974.058     1819735.934      158872.971
     1819979.664      157972.342      1820990.91       156846.27

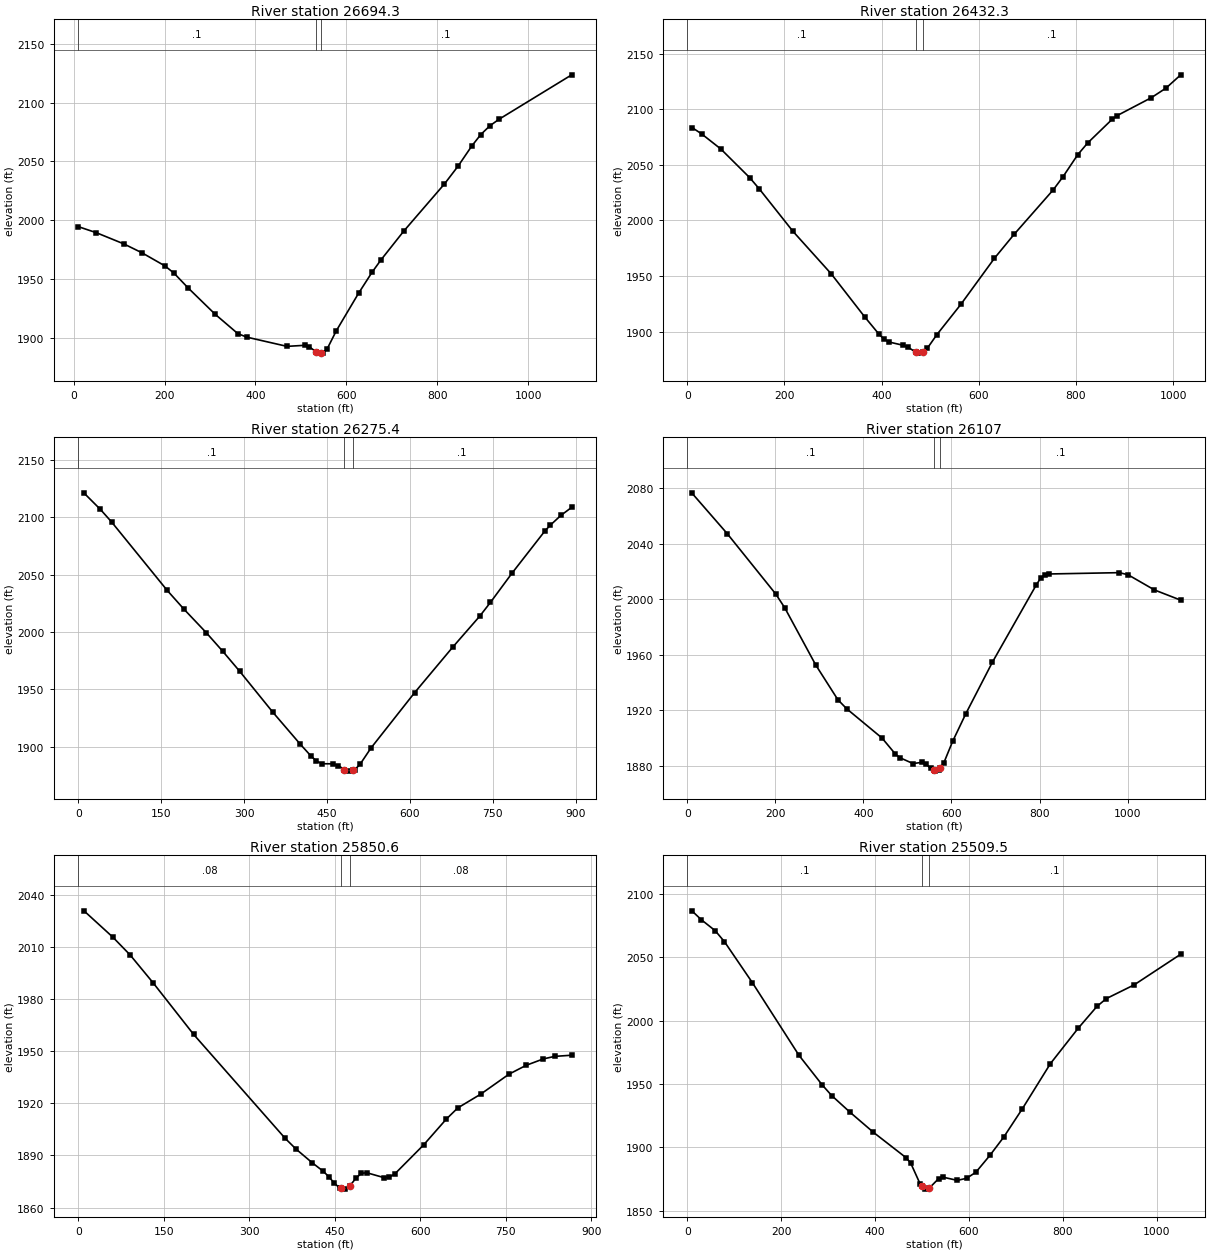
Type RM Length L Ch R = 1 ,26694.3 ,269.1,262,255
XS GIS Cut Line= 4
     1832463.291      171128.606     1832153.259      171271.676
     1831876.163      171476.199     1831528.545      171693.495
#Sta/Elev= 30
      10 1994.48    50.2 1989.26   110.5 1979.76   150.6 1972.15   200.9 1961.05
   220.9 1954.85   251.1 1942.62   311.3 1919.96   361.1 1903.52   380.8 1900.51
   469.4 1892.66   508.7 1893.56   518.6 1892.25   533.3 1888.07   538.3 1886.91
   543.3 1887.04   548.1 1887.16   557.9 1890.64   577.6 1905.74   626.8  1937.8
   656.3 1955.54     676 1966.12   725.8 1990.43   815.8 2030.75   845.8 2045.91
   875.8 2062.96   895.8 2072.78   915.8 2080.22   935.8 2085.74  1095.8 2123.54
#Mann= 3 , 0 , 0
      10      .1       0   533.3    .045       0   543.3      .1       0
Bank Sta=533.3,543.3
XS Rating Curve= 0 ,0
Exp/Cntr=0.3,0.1

Type RM Length L Ch R = 1 ,26432.3 ,160,156.9,153.8
XS GIS Cut Line= 4
     1832104.858      170820.617     1831903.267      171063.917
     1831729.482      171328.071     1831458.376      171599.176
#Sta/Elev= 30
     9.9 2083.52    29.6 2077.82    69.1 2064.25   128.4 2038.52   148.1 2028.45
   217.2 1990.37   296.2 1952.03   365.4 1913.16     395 1897.49   404.9 1893.36
   414.8 1890.73   444.4 1887.73   454.3 1886.02   471.11881.304   474.1 1880.68
   486.1 1881.93   493.8 1884.87   513.6 1897.24     563 1924.48   632.2 1965.99
   672.5 1987.41   753.2 2027.51   773.4 2039.38   803.7 2059.15   823.9 2069.59
   874.3 2090.89   884.4  2094.2     955 2110.36   985.3 2119.01  1015.6 2130.94
#Mann= 3 , 0 , 0
       0      .1       0   471.1    .045       0   486.1      .1       0
Bank Sta=471.1,486.1
XS Rating Curve= 0 ,0
Exp/Cntr=0.3,0.1

Type RM Length L Ch R = 1 ,26275.4 ,167.9,168.4,168.9
XS GIS Cut Line= 4
     1831957.793       170702.92     1831744.045      170982.929
     1831641.447      171207.364     1831476.861      171451.036
#Sta/Elev= 30
    10.1  2121.4    40.3 2106.85    60.4 2095.97     161 2036.27   191.2 2019.95
   231.5 1999.48   261.7 1983.04   291.9 1965.84   352.3 1929.88   401.6 1902.17
   421.4 1891.64   431.2 1887.35   441.1 1884.98   460.8 1884.91   470.7 1883.27
   481.71879.935   490.5 1878.53   496.71879.275   500.3 1879.71   510.2 1884.59
   529.9 1898.74   608.8 1947.01   677.5 1986.57   726.5 2013.67   746.1 2025.83
   785.3 2051.43   844.1  2087.8   853.9 2092.97   873.5 2101.68   893.1 2108.75
#Mann= 3 , 0 , 0
       0      .1       0   481.7    .045       0   496.7      .1       0
Bank Sta=481.7,496.7
XS Rating Curve= 0 ,0
Exp/Cntr=0.3,0.1

Type RM Length L Ch R = 1 ,26107   ,256.7,256.4,256.1
XS GIS Cut Line= 4
     1831858.796      170577.293     1831625.278      170854.185
     1831480.445      171151.338     1831191.483      171466.778
#Sta/Elev= 30
    10.1 2076.61    90.6 2047.28   201.2 2003.63   221.4  1993.8   291.8 1952.58
   342.1 1927.55   362.2 1921.02   442.4 1899.95   472.4 1888.51   482.4 1885.89
   512.5  1881.6   532.5 1882.44   542.5 1881.28   552.5 1878.04   559.71876.685
   562.6 1876.14   572.6 1877.16   574.71878.193   582.6 1882.08   602.6 1897.57
   632.7 1917.58   692.8 1954.54   792.3 2010.13   802.2 2015.06   812.2 2017.38
   822.1 2018.16   981.3 2019.11  1001.2 2017.55  1060.9 2006.65  1120.6 1999.29
#Mann= 3 , 0 , 0
       0      .1       0   559.7    .045       0   574.7      .1       0
Bank Sta=559.7,574.7
XS Rating Curve= 0 ,0
Exp/Cntr=0.3,0.1

Type RM Length L Ch R = 1 ,25850.6 ,344.4,341,337.7
XS GIS Cut Line= 4
     1831611.522      170444.285     1831438.386      170741.394
     1831365.712       170897.43     1831231.051      171220.189
#Sta/Elev= 30
    10.1 2030.69    60.7 2015.55      91 2005.33   131.5 1989.23   202.3 1959.65
     363  1899.8   382.1 1893.62   410.8 1885.67   429.9 1880.84   439.5 1877.75
   449.1 1874.07   458.6 1871.23   461.71871.021   468.2 1870.58   476.71872.536
   487.3 1876.93   496.9 1879.73   506.4 1879.99     536 1877.23     546 1877.47
     556 1879.54   605.9 1896.01   645.9 1910.93   665.9 1917.31   705.9 1925.18
   755.8 1936.74   785.8 1941.81   815.8 1945.48   835.8 1946.95   865.7 1947.62
#Mann= 3 , 0 , 0
       0     .08       0   461.7    .045       0   476.7     .08       0
Bank Sta=461.7,476.7
XS Rating Curve= 0 ,0
Exp/Cntr=0.3,0.1

Type RM Length L Ch R = 1 ,25509.5 ,346.5,349.1,351.6
XS GIS Cut Line= 4
     1831308.775      170282.046     1831125.429      170528.865
      1831028.38      170882.421     1830898.801      171236.262
#Sta/Elev= 30
     9.9 2086.82    29.8 2079.85    59.5 2071.14    79.3 2062.43   138.9    2030
     238 1972.73   287.6 1949.31   307.5 1941.03   347.1 1927.68   396.6 1911.94
     466 1891.94   475.9 1887.65   495.7 1871.42   500.3 1869.43   505.6 1867.14
   515.31867.935   535.4 1875.45   545.3 1876.53     575 1874.05   594.8 1875.67
   614.6 1880.46   644.4 1893.73   674.1 1908.29   713.8 1930.68   773.3 1966.18
   832.8 1994.27   872.4 2011.34   892.3  2017.5   951.8  2028.4  1050.9 2052.58
#Mann= 3 , 0 , 0
       0      .1       0   500.3    .045       0   515.3      .1       0
Bank Sta=500.3,515.3
XS Rating Curve= 0 ,0
Exp/Cntr=0.3,0.1

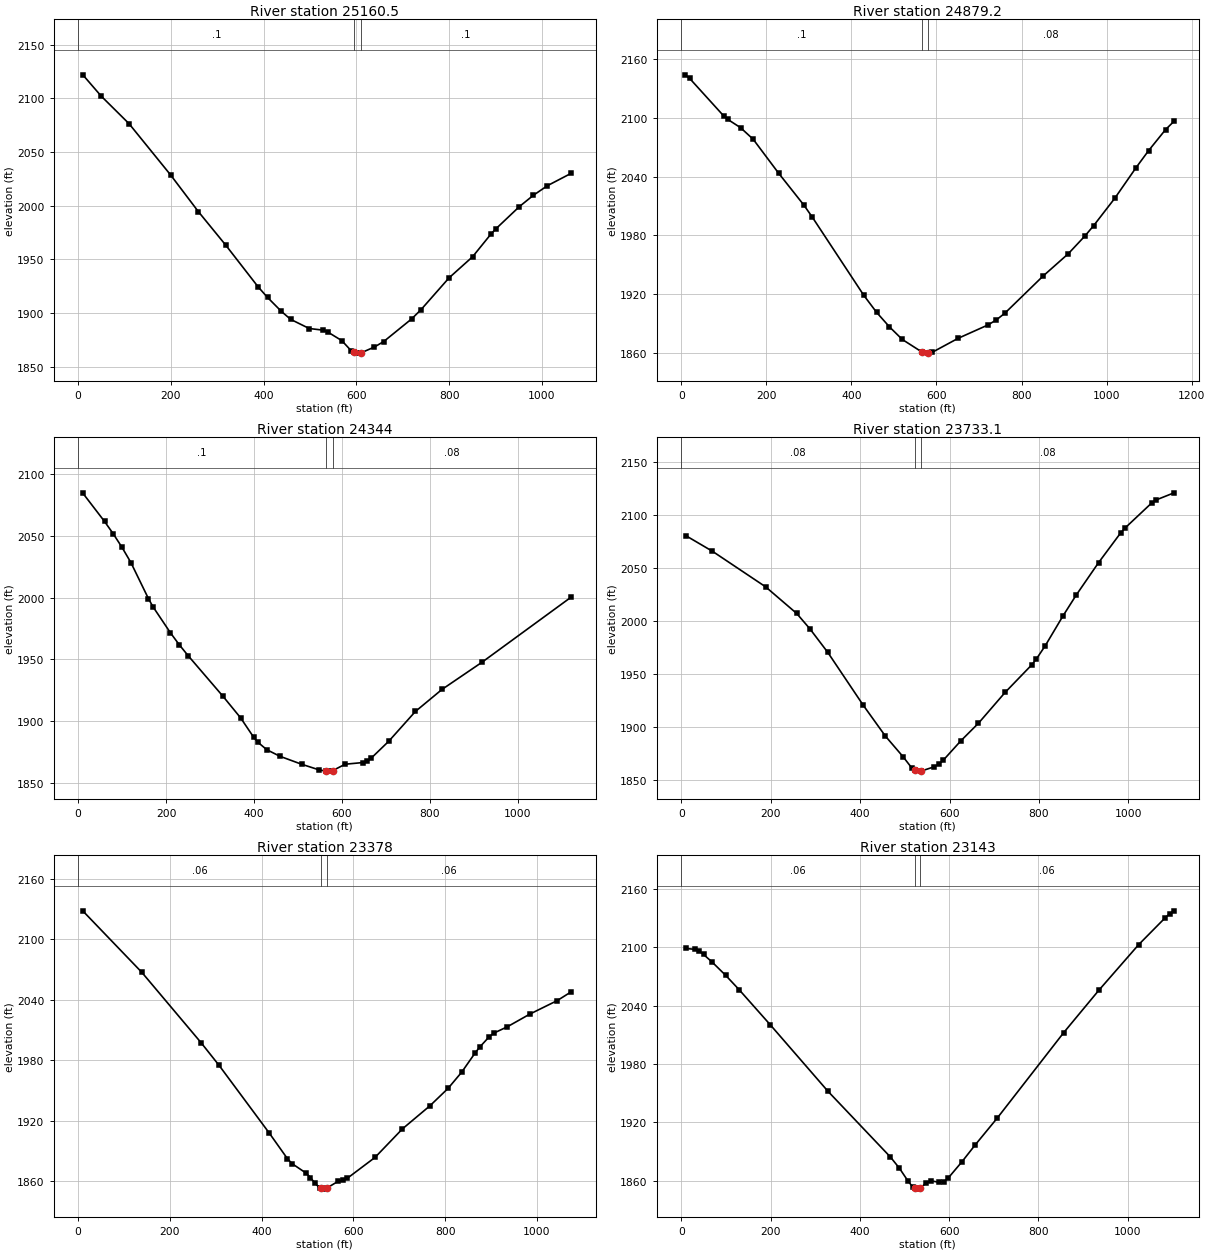
Type RM Length L Ch R = 1 ,25160.5 ,278.4,281.3,284.3
XS GIS Cut Line= 4
      1831122.04      170117.251     1830807.831      170450.698
     1830703.095      170700.782     1830585.533      171012.854
#Sta/Elev= 30
      10 2121.98    49.8 2102.09   109.6 2076.51   199.2 2028.79     259 1994.66
   318.7 1963.09   388.4 1924.31   408.4 1914.62   438.2 1901.64   458.2 1894.21
   498.3 1885.67   528.5 1884.12   538.5 1882.34   568.6 1874.38   588.7 1865.03
   595.61863.445   598.7 1862.73   610.61863.095   638.9 1868.42     659 1873.53
   719.3 1894.64   739.4  1903.2     800 1932.89   850.6 1952.47     891 1974.01
   901.1 1978.59   951.6 1999.23   981.9 2009.81  1012.2 2018.73  1062.8 2030.12
#Mann= 3 , 0 , 0
       0      .1       0   595.6    .045       0   610.6      .1       0
Bank Sta=595.6,610.6
XS Rating Curve= 0 ,0
Exp/Cntr=0.3,0.1

Type RM Length L Ch R = 1 ,24879.2 ,536.7,535.2,533.6
XS GIS Cut Line= 4
     1831001.598      170014.168     1830721.595      170143.498
     1830513.773      170499.765     1830231.387      170833.913
#Sta/Elev= 30
     9.9 2143.93    19.9 2140.18    99.5 2102.05   109.4 2098.35   139.3 2089.96
   169.1 2078.08   228.8 2043.45   288.5 2010.67   308.4 1998.28   429.1 1918.63
   459.3 1901.17   489.5 1886.37   519.7  1873.5   565.21860.857     580 1859.57
   580.21859.588   590.1 1860.44   650.5 1874.63   720.9 1888.33   740.8 1893.54
   760.7 1900.36   850.1 1938.14   909.8 1961.12   949.6 1979.58   969.5 1989.86
  1019.2 2017.84  1068.9 2048.94  1098.7 2066.54  1138.5 2087.96  1158.4 2096.49
#Mann= 3 , 0 , 0
       0      .1       0   565.2    .045       0   580.2     .08       0
Bank Sta=565.2,580.2
XS Rating Curve= 0 ,0
Exp/Cntr=0.3,0.1

Type RM Length L Ch R = 1 ,24344   ,612.7,610.9,609
XS GIS Cut Line= 4
     1830312.548      169493.641     1830299.353      169853.206
     1830150.908      170166.589      1830038.75       170565.74
#Sta/Elev= 30
      10 2084.72      60 2061.54      80 2051.44    99.9  2040.5   119.9 2028.32
   159.9 1999.08   169.9 1992.68   209.9 1971.44   229.9 1961.81   249.9 1953.04
   329.8 1919.92   369.7 1902.56   399.4 1886.84   409.3 1882.74   429.2 1876.82
   458.9 1871.53   508.4 1865.06   548.1 1860.52   563.91859.522   567.9 1859.49
   578.91859.885   607.5 1865.08   647.1 1866.41     657 1867.45   666.9 1870.05
   706.6 1883.65   767.2 1907.75   827.9 1925.63   918.9 1947.62  1121.2 2000.18
#Mann= 3 , 0 , 0
       0      .1       0   563.9    .045       0   578.9     .08       0
Bank Sta=563.9,578.9
XS Rating Curve= 0 ,0
Exp/Cntr=0.3,0.1

Type RM Length L Ch R = 1 ,23733.1 ,350,355.1,360.2
XS GIS Cut Line= 4
      1829912.06      169354.601     1829687.842      169706.076
     1829603.313      169938.974     1829428.438      170339.877
#Sta/Elev= 30
     9.9 2080.32    69.5 2065.58   188.6 2032.03   258.1 2006.94   287.9 1992.32
   327.6 1970.29     407 1920.41   456.5 1891.35   496.2 1871.84     516 1861.06
   522.61859.427   535.8 1858.34   537.11858.473   565.6 1862.42   575.5 1864.78
   585.4 1868.37     625 1886.79   664.7 1903.51   724.3 1932.55     784 1958.57
   793.9 1963.88   813.8 1976.36   853.5 2004.49   883.4 2024.35   933.1 2054.73
   982.8 2082.92   992.7 2087.53  1052.3 2111.15  1062.3 2113.95    1102  2120.6
#Mann= 3 , 0 , 0
       0     .08       0   522.6    .045       0   537.1     .08       0
Bank Sta=522.6,537.1
XS Rating Curve= 0 ,0
Exp/Cntr=0.3,0.1

Type RM Length L Ch R = 1 ,23378   ,240.9,235,229.2
XS GIS Cut Line= 4
     1829524.143       169229.74     1829369.101      169658.579
     1829250.345      169833.414     1829190.967      170235.863
#Sta/Elev= 30
     9.9 2128.17   138.8 2067.11   267.7 1997.46   307.3 1974.75   416.4 1907.77
     456 1882.38   466.1  1877.4   496.3  1868.1   506.3 1863.55   516.4 1857.71
   526.5 1853.32  528.581853.054   536.5 1852.05   542.51853.236   566.7 1859.81
   576.8 1860.65   586.8 1862.85   647.2 1883.55     707 1911.88   766.6 1934.64
   806.3 1951.97     836 1968.06   865.8 1987.47   875.7 1993.17   895.6    2003
   905.5 2006.71   935.3 2013.07   984.9 2025.78  1044.4 2039.13  1074.2 2047.65
#Mann= 3 , 0 , 0
       0     .06       0  528.58    .045       0   542.5     .06       0
Bank Sta=528.58,542.5
XS Rating Curve= 0 ,0
Exp/Cntr=0.3,0.1

Type RM Length L Ch R = 1 ,23143   ,270.7,271.4,272.1
XS GIS Cut Line= 4
     1829324.022       169140.07     1829170.942      169430.842
     1829065.614       169764.14     1828842.909      170126.785
#Sta/Elev= 30
      10 2098.97    29.9 2098.11    39.8 2096.22    49.8 2092.86    69.7 2084.74
    99.6 2071.26   129.5 2056.63   199.2 2020.56   328.6 1952.08   468.4 1884.52
   488.4 1873.09   508.4 1859.44   518.4 1853.68   523.61852.513   528.3 1851.46
   535.7 1852.94   548.3 1857.47   558.3 1860.04   578.3 1858.48   588.3 1859.14
   598.3 1863.08   628.2 1879.33   658.2 1896.85   707.8 1924.57   856.3 2012.26
   935.5  2056.1  1024.5 2102.91  1083.9 2130.52  1093.8 2134.64  1103.7 2137.69
#Mann= 3 , 0 , 0
       0     .06       0   523.6    .045       0   535.7     .06       0
Bank Sta=523.6,535.7
XS Rating Curve= 0 ,0
Exp/Cntr=0.3,0.1

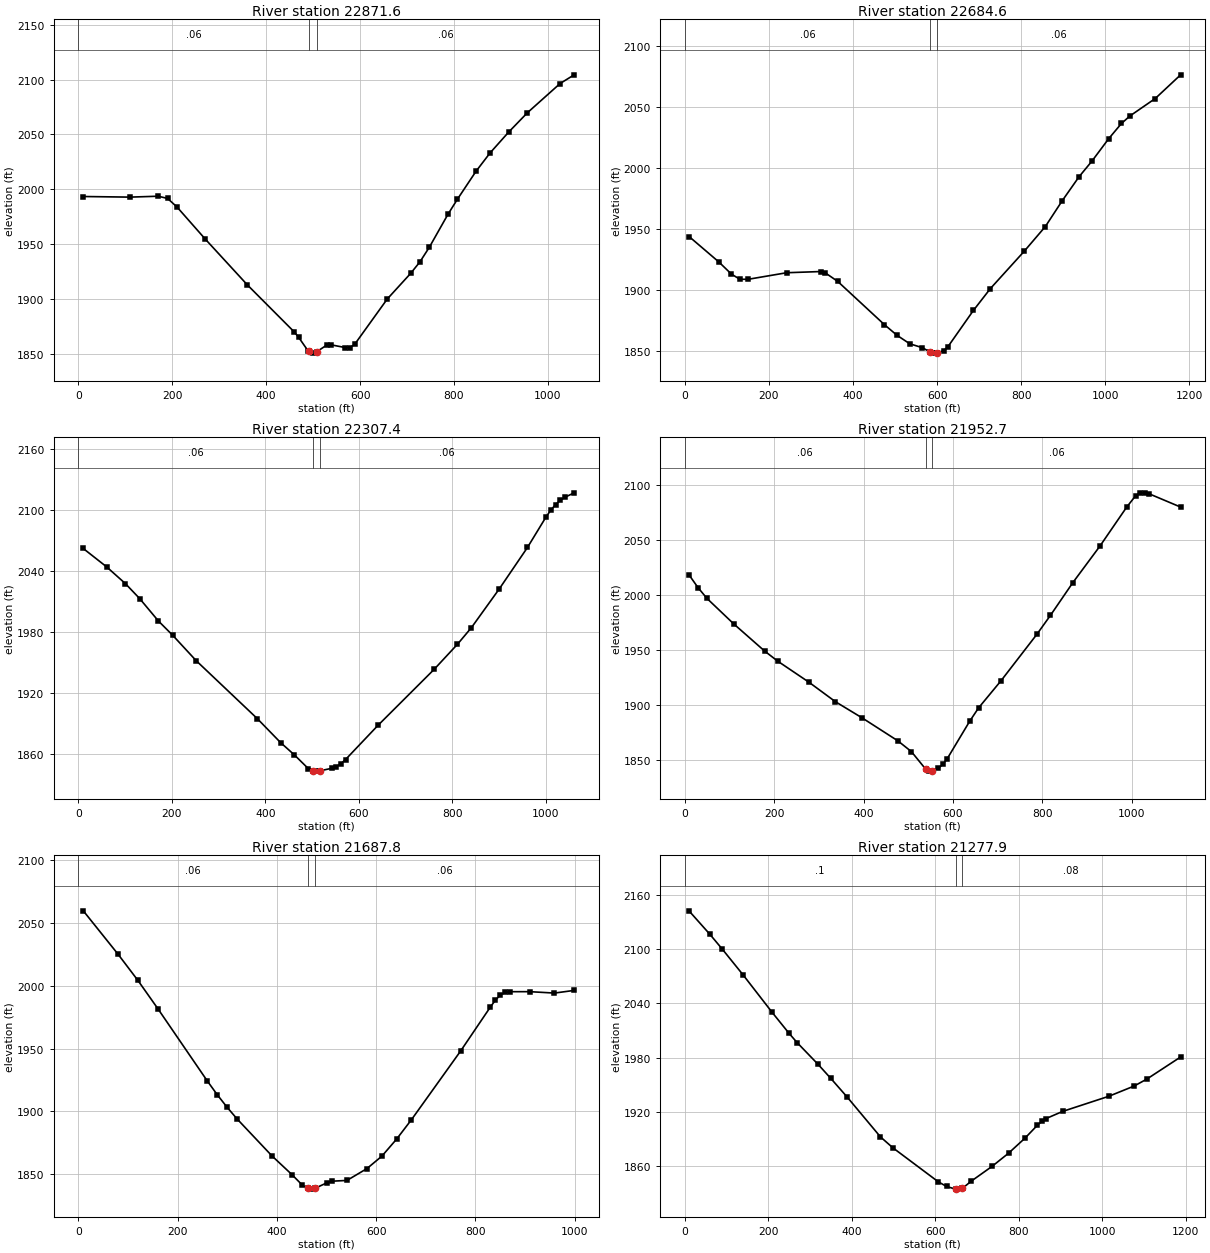
Type RM Length L Ch R = 1 ,22871.6 ,185.4,187,188.6
XS GIS Cut Line= 4
     1829144.784      169058.204     1828910.572      169394.678
     1828831.402      169618.994     1828732.439      170014.846
#Sta/Elev= 30
      10 1993.31     110 1992.75     170 1993.57     190 1991.57     210 1983.79
     270  1954.6     360 1912.64   459.5 1869.87   469.4 1864.67   489.3 1852.43
   491.7 1851.94   499.2  1850.4   507.61851.623   528.9 1857.72   538.8 1857.91
   568.5 1855.48   578.5 1855.51   588.4 1858.36   657.8 1899.74   707.6 1923.11
   727.5 1933.69   747.4 1946.96   787.2 1977.11   807.1 1990.72   846.9 2016.32
   876.7 2033.01   916.5 2052.12   956.4 2069.77    1026 2096.42  1055.9 2104.34
#Mann= 3 , 0 , 0
       0     .06       0   491.7    .045       0   507.6     .06       0
Bank Sta=491.7,507.6
XS Rating Curve= 0 ,0
Exp/Cntr=0.3,0.1

Type RM Length L Ch R = 1 ,22684.6 ,382.5,377.1,371.8
XS GIS Cut Line= 4
     1829006.236      168929.552     1828788.518      169233.038
     1828646.671      169556.317     1828626.878      170008.248
#Sta/Elev= 30
    10.1 1943.67    80.8 1922.88     111 1912.84   131.2 1908.62   151.4 1908.68
   242.3 1914.01     323 1914.98   333.1 1914.12   363.4 1906.96   474.4 1871.55
   504.6 1862.77   534.9 1855.83   565.1  1852.6   583.71849.002   595.4 1848.18
   598.71848.319   615.6 1850.25   625.7 1853.46   686.2 1883.14   726.5 1901.01
     807 1931.58   857.2  1951.8   897.4 1972.96   937.6 1992.69   967.8 2005.29
    1008 2023.81  1038.2 2036.21  1058.3 2042.35  1118.6 2056.66  1178.9 2076.05
#Mann= 3 , 0 , 0
       0     .06       0   583.7    .045       0   598.7     .06       0
Bank Sta=583.7,598.7
XS Rating Curve= 0 ,0
Exp/Cntr=0.3,0.1

Type RM Length L Ch R = 1 ,22307.4 ,359.1,354.7,350.2
XS GIS Cut Line= 4
     1828297.002      168781.107     1828390.346      169131.875
     1828343.321      169416.159       1828300.3      169823.518
#Sta/Elev= 30
    10.1 2062.25    60.5 2044.02   100.8 2027.44   131.1  2012.8   171.4 1990.62
   201.7 1976.67   252.1 1951.55   382.8 1894.46   432.5 1870.92   462.3 1858.64
   492.1 1845.15   501.81843.055     512 1842.71   517.61843.102   541.8 1845.45
   551.8 1847.08   561.7 1850.01   571.6 1854.11   641.2 1887.89     761 1942.92
     811 1967.71   840.9 1984.11   900.9 2022.54   960.8 2063.12  1000.8 2093.38
  1010.8 2099.91  1020.8 2105.34  1030.8 2109.47  1040.8 2112.56  1060.7 2116.96
#Mann= 3 , 0 , 0
       0     .06       0   501.8    .045       0   517.6     .06       0
Bank Sta=501.8,517.6
XS Rating Curve= 0 ,0
Exp/Cntr=0.3,0.1

Type RM Length L Ch R = 1 ,21952.7 ,266.3,264.9,263.4
XS GIS Cut Line= 4
     1827908.674      168739.569      1828006.71      169134.075
      1828025.72      169484.801     1828113.886       169825.27
#Sta/Elev= 30
     9.9 2017.83    29.7 2006.45    49.6 1996.72   109.1 1973.73   178.5 1948.97
   208.2 1939.69   277.6 1920.71   337.1 1902.95   396.6 1888.33   476.8 1867.43
   506.9 1857.72   538.71841.902     547 1839.96   553.71840.191   567.1 1842.43
   577.1 1846.08   587.1 1851.19   637.3 1885.15   657.4  1897.4   707.6 1922.02
   787.9 1964.21     818 1981.26   868.3 2011.08   928.6 2044.06   988.9 2079.69
    1009 2090.03    1019 2092.32  1029.1 2092.55  1039.1 2091.64  1109.4 2079.62
#Mann= 3 , 0 , 0
       0     .06       0   538.7    .045       0   553.7     .06       0
Bank Sta=538.7,553.7
XS Rating Curve= 0 ,0
Exp/Cntr=0.3,0.1

Type RM Length L Ch R = 1 ,21687.8 ,423.9,409.9,394.1
XS GIS Cut Line= 4
     1827485.093      168945.221     1827736.624      169188.505
     1827769.611      169448.283     1827951.044       169790.53
#Sta/Elev= 30
      10 2059.51      80 2025.03     120  2004.2     160 1981.84     260 1924.17
   279.9  1913.3   299.9 1903.25   319.9 1894.04   390.2 1864.65   430.5 1849.75
   450.7 1841.68   461.91838.732   470.8 1838.22   476.91838.866     501 1843.26
   511.1 1844.53   541.3 1845.13   581.6 1854.55   611.8 1864.48   641.6  1878.1
   671.4 1893.48   770.7 1948.21   830.3 1982.98   840.2 1988.35   850.2 1992.46
   860.1 1994.57     870 1995.21   909.8 1995.23   959.4 1994.11   999.2 1996.23
#Mann= 3 , 0 , 0
       0     .06       0   461.9    .045       0   476.9     .06       0
Bank Sta=461.9,476.9
XS Rating Curve= 0 ,0
Exp/Cntr=0.3,0.1

Type RM Length L Ch R = 1 ,21277.9 ,280.2,295.1,310.1
XS GIS Cut Line= 4
     1827202.208      169031.916     1827412.932      169450.757
     1827706.522      169731.152     1827962.956      169911.269
#Sta/Elev= 30
      10 2142.56    59.9 2116.66    89.8 2100.15   139.7 2071.58   209.5 2029.97
   249.4 2007.09   269.3 1996.49   319.2 1972.58   349.2 1957.27   389.1 1936.25
   468.9 1892.11   498.6 1880.04   607.5 1842.37   627.3  1837.2   648.81834.256
     652 1834.25   663.81835.258   666.9 1835.72   686.7 1843.17   736.2 1859.42
   775.8 1874.03   815.4  1890.8   845.1 1905.09     855 1909.19   864.9 1912.26
   905.2  1920.3  1016.4 1937.16    1077 1948.49  1107.3 1956.18  1188.2 1980.65
#Mann= 3 , 0 , 0
       0      .1       0   648.8    .045       0   663.8     .08       0
Bank Sta=648.8,663.8
XS Rating Curve= 0 ,0
Exp/Cntr=0.3,0.1

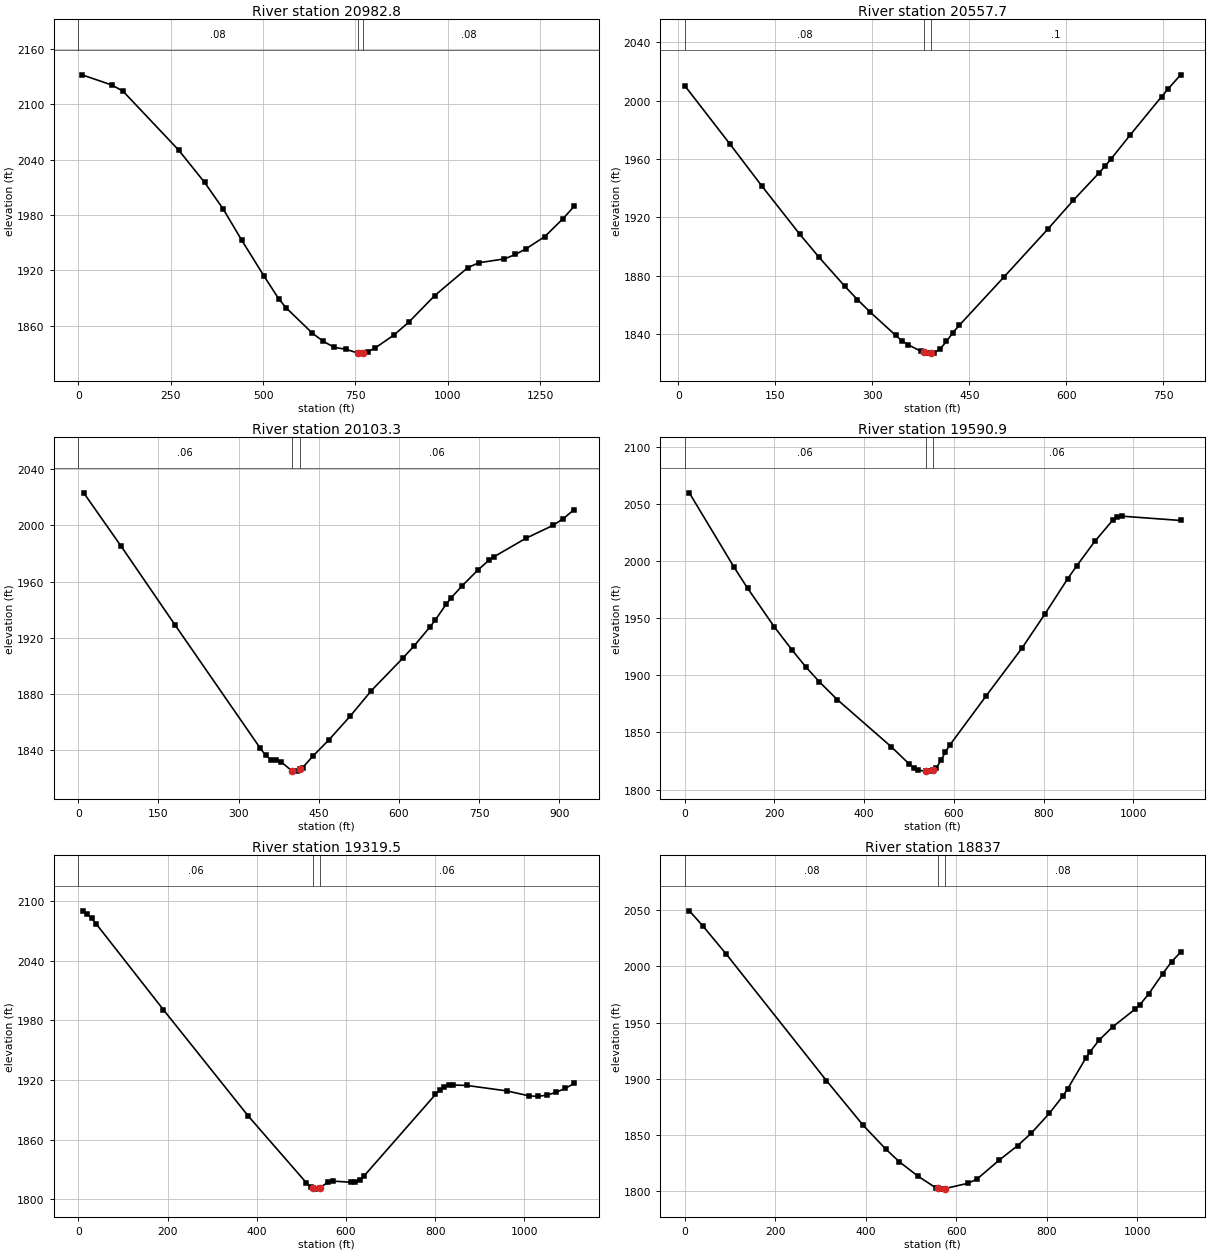
Type RM Length L Ch R = 1 ,20982.8 ,414.5,425.1,435.6
XS GIS Cut Line= 4
     1827078.495      169069.764      1827326.87      169619.028
     1827351.611      169990.139     1827335.117      170357.127
#Sta/Elev= 30
      10 2131.85    90.4 2120.85   120.6 2114.26   271.3 2050.41   341.6 2015.32
   391.8 1986.63   442.1 1952.72   502.3 1913.97   542.5 1889.01   562.6 1879.28
     633 1852.03   663.1 1842.99   693.3 1836.41   723.4  1834.5   756.21830.378
   763.6 1830.24   771.21830.472   783.8 1831.72   803.9 1835.95   854.1 1849.83
   894.3 1863.72   964.7 1892.61  1054.2 1922.89    1084 1928.17  1153.5 1932.36
  1183.2 1937.17    1213 1943.61  1262.7 1956.58  1312.3 1976.11  1342.1 1989.37
#Mann= 3 , 0 , 0
       0     .08       0   756.2    .045       0   771.2     .08       0
Bank Sta=756.2,771.2
XS Rating Curve= 0 ,0
Exp/Cntr=0.3,0.1

Type RM Length L Ch R = 1 ,20557.7 ,448.9,454.4,459.9
XS GIS Cut Line= 4
     1827043.883      169328.703     1826982.031       169588.48
     1826866.574      169827.641     1826845.957      170070.925
#Sta/Elev= 30
     9.9 2010.28    79.1 1970.63   128.6 1941.75   187.9 1908.28   217.6 1892.57
   257.1 1872.83   276.9 1863.57   296.5 1855.02   335.9 1839.04   345.7 1835.27
   355.6 1832.51   375.2 1828.07   380.1 1827.44   385.1  1826.8   390.1 1826.86
   394.9 1826.91   404.7 1829.58   414.6 1834.84   424.4 1840.77   434.3 1845.83
   503.1 1878.82   571.7 1912.04   610.7  1931.6   649.8 1950.08   659.6 1954.94
   669.3 1960.09   698.6 1976.39   747.5 2002.89   757.2 2007.98   776.8 2017.77
#Mann= 3 , 0 , 0
     9.9     .08       0   380.1    .045       0   390.1      .1       0
Bank Sta=380.1,390.1
XS Rating Curve= 0 ,0
Exp/Cntr=0.3,0.1

Type RM Length L Ch R = 1 ,20103.3 ,529.2,512.5,495.7
XS GIS Cut Line= 4
     1826874.821      169167.888     1826658.242      169331.114
     1826474.846      169538.999     1826417.117      169914.234
#Sta/Elev= 30
      10 2023.18    80.4 1985.01   180.8 1929.25   340.5 1841.42   350.4 1836.38
   360.3 1833.34   370.2 1832.86   380.1 1831.57   400.11825.139   409.8  1825.1
   415.11826.393   419.7 1827.52   439.5 1835.96   469.2 1847.42   508.8 1864.19
   548.4 1882.36   608.4 1905.91   628.3 1914.14   658.3 1927.77   668.3 1932.73
   688.3 1943.78   698.3 1948.61   718.3 1956.97   748.2 1968.34   768.2 1975.07
   778.2 1977.72   838.2 1990.91   888.1 1999.93   908.1 2004.85   928.1 2011.31
#Mann= 3 , 0 , 0
       0     .06       0   400.1    .045       0   415.1     .06       0
Bank Sta=400.1,415.1
XS Rating Curve= 0 ,0
Exp/Cntr=0.3,0.1

Type RM Length L Ch R = 1 ,19590.9 ,269.7,271.3,272.4
XS GIS Cut Line= 4
     1826029.694      168811.118     1826062.365      169219.658
     1826095.353      169520.671     1826049.924      169911.128
#Sta/Elev= 30
      10 2059.61     110 1994.46   139.9 1976.26   199.9 1942.22   239.9 1921.77
   269.9 1907.33   299.9 1894.36   339.9  1878.8   460.3 1837.53   500.7 1822.33
   510.8 1818.91   520.9  1816.9   536.91816.246   541.1 1816.17   551.2 1816.41
   553.51817.066   561.3 1819.29   571.3 1825.66   581.4    1833   591.5 1839.22
   672.3 1882.11     753 1924.31   803.4 1953.78   853.8 1984.38   873.9 1995.65
   914.2 2017.07   954.6  2035.8   964.6 2038.58   974.7  2039.2  1105.8 2035.42
#Mann= 3 , 0 , 0
       0     .06       0   536.9    .045       0   553.5     .06       0
Bank Sta=536.9,553.5
XS Rating Curve= 0 ,0
Exp/Cntr=0.3,0.1

Type RM Length L Ch R = 1 ,19319.5 ,482.5,482.6,482.6
XS GIS Cut Line= 4
     1825666.648      168825.641     1825848.887      169148.975
     1825843.957      169518.382     1825839.833      169889.493
#Sta/Elev= 30
      10 2090.08    20.1 2086.85    30.1 2082.46    40.1 2076.92   190.6 1990.78
   381.1 1883.79   510.9 1816.96   520.9 1812.29   525.81811.369   530.9 1810.41
   540.81811.766   560.9 1817.51   570.9  1818.5   610.8  1817.3   620.8 1817.54
   630.8 1819.47   640.7 1823.67   800.8 1905.58   810.8 1910.05   820.8  1913.2
   830.9 1914.62   840.9 1915.03     871 1914.61   961.3 1909.07  1011.4 1904.04
  1031.5 1903.65  1051.5 1904.96  1071.6 1907.75  1091.7 1911.64  1111.7 1916.61
#Mann= 3 , 0 , 0
       0     .06       0   525.8    .045       0   540.8     .06       0
Bank Sta=525.8,540.8
XS Rating Curve= 0 ,0
Exp/Cntr=0.3,0.1

Type RM Length L Ch R = 1 ,18837   ,500.5,499.8,498.8
XS GIS Cut Line= 4
     1825291.413      168842.135     1825382.129      169266.851
     1825378.006       169588.48     1825460.475      169918.357
#Sta/Elev= 30
    10.1 2049.41    40.4 2035.72    90.9 2011.29   313.1 1898.48   393.9 1858.93
   444.3 1837.61   474.5 1826.25   514.7 1813.77   554.9 1803.15   559.61802.625
     565 1802.02   574.61802.452   625.3 1807.17   645.4 1810.76   695.6 1828.03
   735.8 1840.68     766 1851.79     806 1869.48     836  1884.9     846 1890.98
     886 1918.21     896 1924.23     916  1934.6     946 1946.31     996 1962.22
    1006 1965.95    1026 1975.88    1056 1993.31    1076 2004.13    1096 2012.65
#Mann= 3 , 0 , 0
       0     .08       0   559.6    .045       0   574.6     .08       0
Bank Sta=559.6,574.6
XS Rating Curve= 0 ,0
Exp/Cntr=0.3,0.1

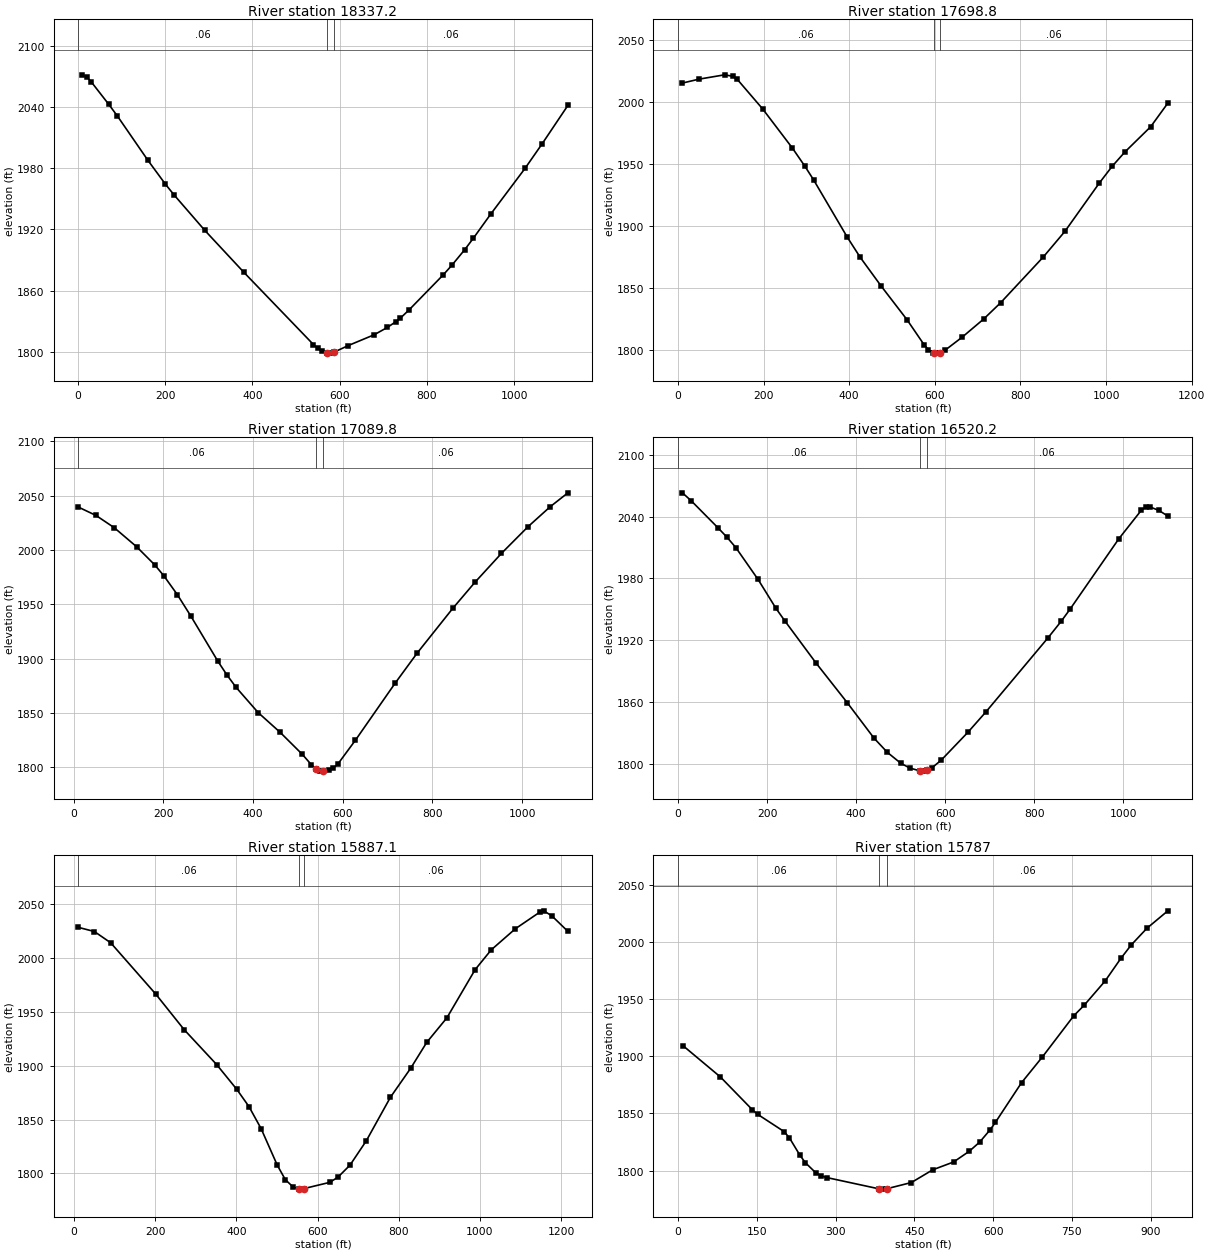
Type RM Length L Ch R = 1 ,18337.2 ,621.1,638.4,655.7
XS GIS Cut Line= 4
     1824962.683       168825.13     1824925.629      169143.766
     1824920.302      169571.987     1824840.558      169937.852
#Sta/Elev= 30
      10 2071.38      20 2069.27    30.1  2064.6    70.2  2042.6    90.2 2031.05
   160.4 1987.53   200.5  1964.2   220.5  1953.6   290.7 1919.01   380.5 1877.82
   539.9 1807.12   549.8 1803.41   559.8 1800.52   571.91798.871   579.7 1798.73
   586.91799.633   619.6 1806.12   679.3 1816.75   709.2 1823.85   729.1 1829.58
   739.1 1832.96   758.9 1840.95   837.7 1875.48   857.4 1884.84     887 1900.17
   906.7 1911.33   946.1 1934.72    1025 1979.63  1064.4 2003.81  1123.5 2041.45
#Mann= 3 , 0 , 0
       0     .06       0   571.9    .045       0   586.9     .06       0
Bank Sta=571.9,586.9
XS Rating Curve= 0 ,0
Exp/Cntr=0.3,0.1

Type RM Length L Ch R = 1 ,17698.8 ,601.6,608.9,616.3
XS GIS Cut Line= 4
      1824812.55      168754.379     1824517.313      169032.484
     1824227.561      169275.098     1824007.363      169560.754
#Sta/Elev= 30
     9.9 2015.62    49.5 2018.83   108.8  2022.3   128.6 2021.11   138.5 2018.65
   197.9 1994.76   267.1  1963.3   296.8 1948.41   316.6 1937.69   395.7 1891.21
   425.5 1875.18   475.2 1851.63   534.9 1824.81   574.7 1804.67   584.6 1800.72
   594.6 1798.28   598.11798.116   604.5 1797.81   613.11798.122   624.4 1800.28
   664.2 1810.78   713.9 1825.26   753.7 1838.47   853.6 1875.47   903.7 1895.98
   983.9 1934.89  1013.9  1948.4    1044  1960.1  1104.1 1980.42  1144.2 1999.47
#Mann= 3 , 0 , 0
       0     .06       0   598.1    .045       0   613.1     .06       0
Bank Sta=598.1,613.1
XS Rating Curve= 0 ,0
Exp/Cntr=0.3,0.1

Type RM Length L Ch R = 1 ,17089.8 ,570.4,569.6,568.8
XS GIS Cut Line= 4
     1824631.321      168398.608     1824305.323      168556.668
     1823943.043      168685.443     1823663.054      168904.573
#Sta/Elev= 30
    10.1 2039.54    50.3 2031.66    90.6  2020.5   140.9 2002.83   181.1 1986.21
   201.3 1976.24   231.5 1958.83   261.7 1939.03     322 1897.44   342.2 1884.85
   362.3 1873.61   411.6 1850.34   460.9 1832.05   510.2 1811.85   529.9 1802.52
   541.7 1797.97  549.66 1796.43   556.71796.474   569.3 1797.39   579.2 1799.22
     589 1802.73   628.5 1824.85   717.2 1877.42   766.5 1905.22   845.5 1946.16
   894.9 1970.13   954.2 1996.82  1013.4 2021.36  1062.8 2039.72  1102.3 2052.51
#Mann= 3 , 0 , 0
    10.1     .06       0   541.7    .045       0   556.7     .06       0
Bank Sta=541.7,556.7
XS Rating Curve= 0 ,0
Exp/Cntr=0.3,0.1

Type RM Length L Ch R = 1 ,16520.2 ,631,633.1,635.3
XS GIS Cut Line= 4
     1824396.814      167931.868     1824085.096       168039.32
     1823712.129      168186.505      1823346.79      168237.551
#Sta/Elev= 30
      10 2063.05      30 2055.22    89.9 2029.02   109.9 2019.97   129.9 2009.85
   179.8 1978.89   219.8 1950.91   239.8 1938.67   309.7  1897.8   379.8 1859.25
     440 1824.72   470.1 1810.83   500.1 1800.31   520.2 1795.69   543.21792.836
   550.2 1792.63   558.21793.376   570.3 1795.95   590.3 1803.03   650.5 1830.22
   690.6 1849.84   830.4 1922.04   860.3 1938.27   880.2 1950.04   989.9 2018.57
  1039.7 2045.89  1049.7 2049.45  1059.7 2049.33  1079.6 2045.92  1099.6 2040.49
#Mann= 3 , 0 , 0
       0     .06       0   543.2    .045       0   558.2     .06       0
Bank Sta=543.2,558.2
XS Rating Curve= 0 ,0
Exp/Cntr=0.3,0.1

Type RM Length L Ch R = 1 ,15887.1 ,101.1,100.1,99
XS GIS Cut Line= 4
     1824225.567      167482.451     1823904.097      167475.738
     1823491.751      167591.195     1823228.059      167976.739
#Sta/Elev= 30
      10 2028.81    50.2 2024.87    90.4 2014.41     201 1966.91   271.3  1933.7
   351.4 1901.24   401.2 1878.11   431.1 1862.14     461 1841.66   500.8 1807.71
   520.7 1794.21   540.6 1787.14   555.5 1785.49   560.5 1785.43   565.5 1785.83
   630.2 1791.73   650.2 1796.52     680 1807.73   719.9 1830.21   779.6 1870.83
   829.3 1897.68     869 1921.81   918.7 1944.66   988.3 1989.48    1028 2007.86
  1087.6  2027.5  1147.3 2042.82  1157.2  2044.1  1177.1 2039.46  1216.8 2024.99
#Mann= 3 , 0 , 0
      10     .06       0   555.5    .045       0   565.5     .06       0
Bank Sta=555.5,565.5
XS Rating Curve= 0 ,0
Exp/Cntr=0.3,0.1

Type RM Length L Ch R = 1 ,15787   ,212.1,200.2,188.2
XS GIS Cut Line= 4
      1824034.17      167362.045     1823764.848      167404.795
     1823563.926      167473.194     1823288.191      167825.877
#Sta/Elev= 30
    10.1 1909.02    80.8 1881.89   141.4 1853.34   151.5  1849.3     202 1834.17
   212.1 1828.73   232.3  1813.4   242.4 1807.04   262.6 1798.03   272.7 1795.42
   282.8 1794.03   383.11784.077     394 1783.87   398.11784.264   444.5 1789.66
   484.9 1800.73   524.7 1807.58   554.6 1816.97   574.5 1825.02   594.4 1835.79
   604.3 1842.19   654.1 1876.88   693.9 1899.44   753.5 1935.34   773.4 1944.58
   813.2 1965.75   843.1 1985.45     863 1997.29   892.8 2011.83   932.6 2027.06
#Mann= 3 , 0 , 0
       0     .06       0   383.1    .045       0   398.1     .06       0
Bank Sta=383.1,398.1
XS Rating Curve= 0 ,0
Exp/Cntr=0.3,0.1