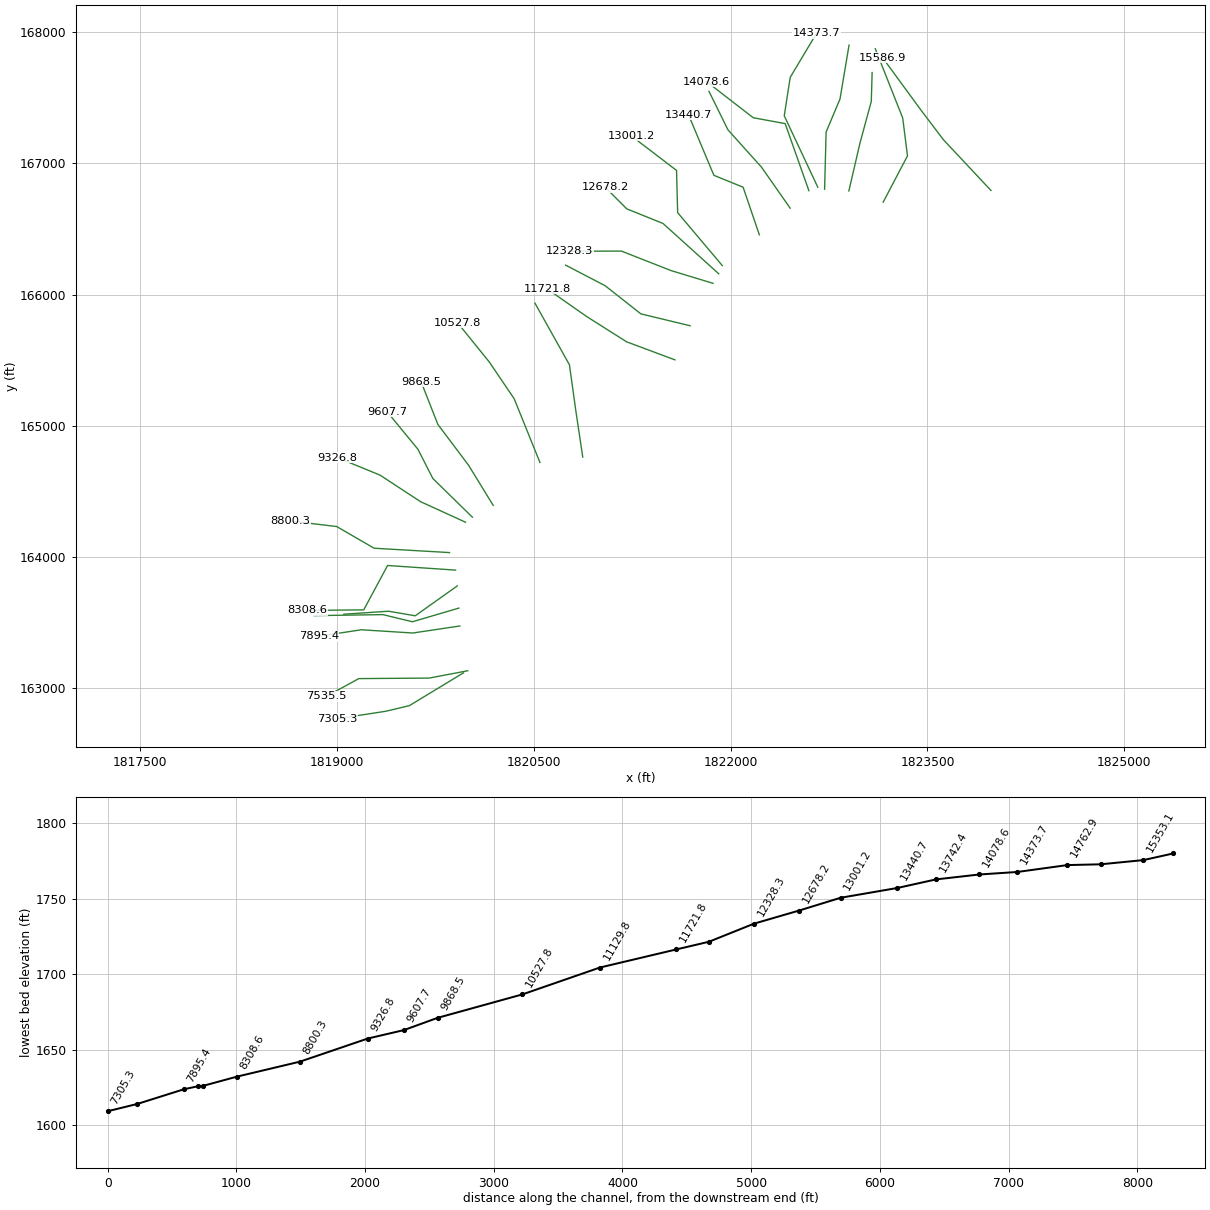
HEC-RAS study Laurel Branch B.prj: Laurel Branch B

--- Laurel Branch B.g01 (geometry) --- (continued)

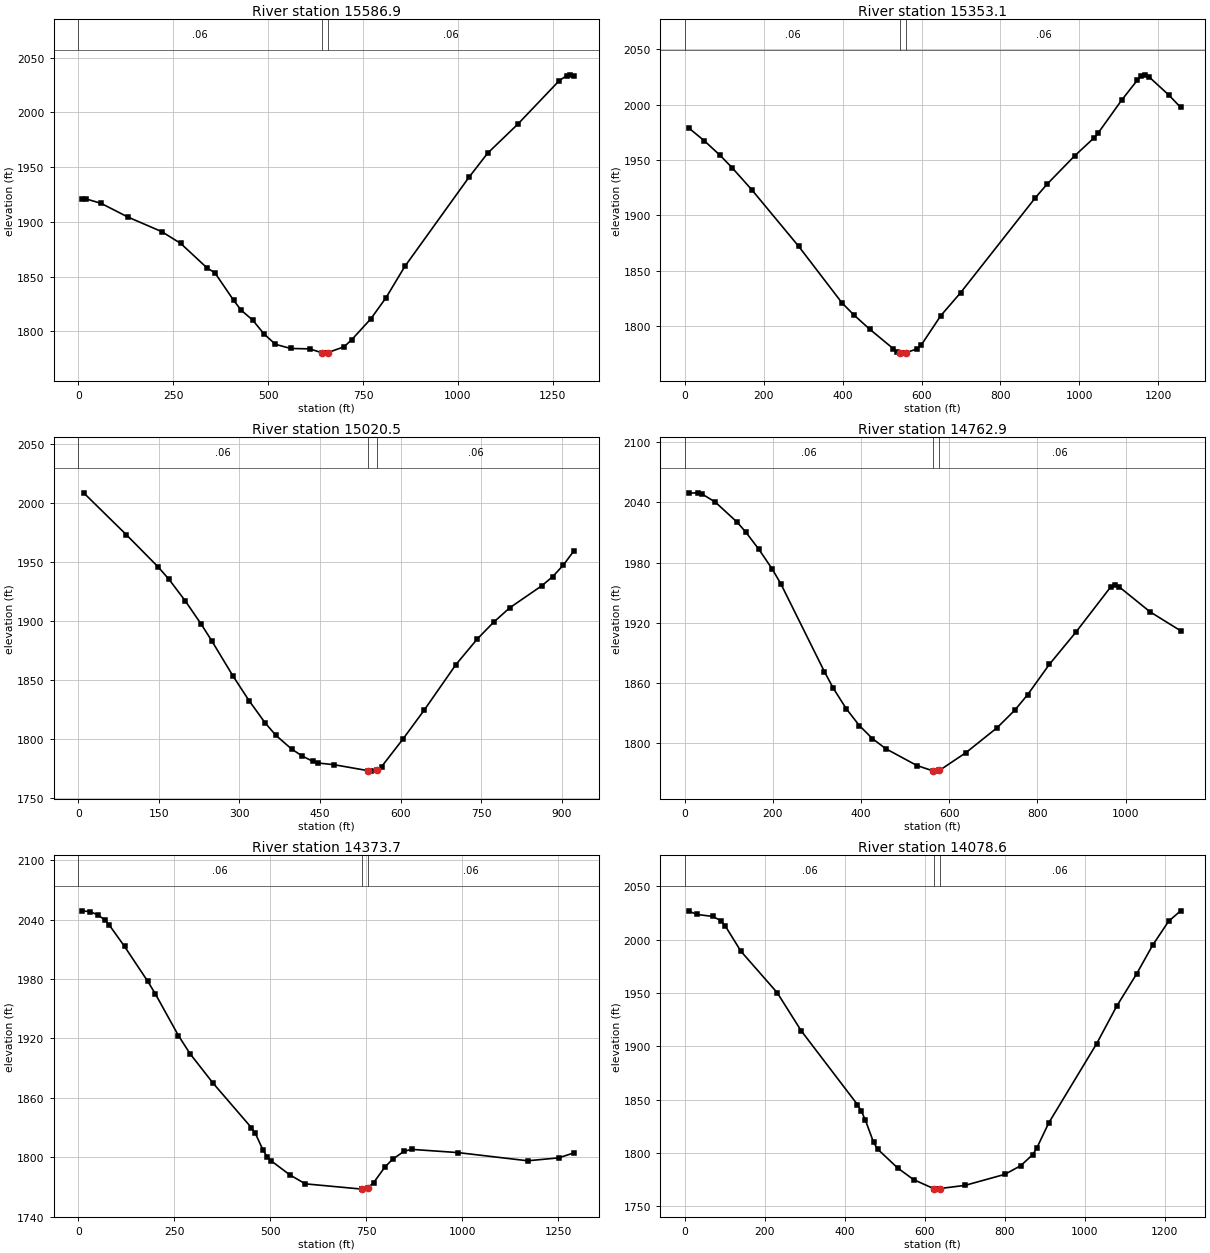
Type RM Length L Ch R = 1 ,15586.9 ,244.4,233.8,223.2
XS GIS Cut Line= 4
     1823984.277      166792.776     1823622.296      167178.873
     1823452.351      167403.048     1823159.586      167803.023
#Sta/Elev= 30
      10 1920.44      20 1920.95    59.9  1916.9   129.8  1904.5   219.7 1891.04
   269.6  1880.3   339.5 1857.76   359.5 1853.57   409.4 1828.16   429.4 1819.12
   459.3 1810.27   489.3 1797.51   519.3 1788.11   559.4 1784.32   609.6 1783.96
   642.61780.282   649.8 1780.07   657.61780.612     700 1785.85   720.1  1792.3
   770.4 1811.32   810.6 1830.71   860.1 1859.24  1028.7 1940.52  1078.2 1962.68
  1157.5 1989.13  1266.6 2028.83  1286.4  2033.6  1296.3 2034.28  1306.2 2032.81
#Mann= 3 , 0 , 0
       0     .06       0   642.6    .045       0   657.6     .06       0
Bank Sta=642.6,657.6
XS Rating Curve= 0 ,0
Exp/Cntr=0.3,0.1

Type RM Length L Ch R = 1 ,15353.1 ,340.5,332.5,324.5
XS GIS Cut Line= 4
      1823162.89       166703.74      1823348.04      167056.386
     1823311.703      167344.945     1823102.801      167872.631
#Sta/Elev= 30
      10 1978.92    49.8 1967.23    89.6 1954.14   119.5 1943.18   169.3 1923.32
   288.8 1871.99   398.3 1821.05   428.4 1810.15   468.5  1797.3   528.7 1779.54
   538.7 1776.87   545.71776.002   548.7 1775.63   560.71775.992   588.8 1779.52
   598.9 1782.74     649 1809.53   699.1 1830.21   888.3 1915.82   918.1 1928.14
   987.8 1953.62  1037.6  1970.1  1047.6 1974.31  1107.3 2004.05  1147.1 2022.13
  1157.1 2025.78  1167.1 2026.89    1177 2024.92  1226.8 2008.65  1256.7 1997.52
#Mann= 3 , 0 , 0
       0     .06       0   545.7    .045       0   560.7     .06       0
Bank Sta=545.7,560.7
XS Rating Curve= 0 ,0
Exp/Cntr=0.3,0.1

Type RM Length L Ch R = 1 ,15020.5 ,260.5,257.7,254.8
XS GIS Cut Line= 4
     1822901.308      166789.201     1822986.807      167156.847
     1823072.306      167471.056     1823078.719      167691.216
#Sta/Elev= 30
     9.9 2008.75    89.4 1973.22     149 1945.75   168.9 1935.35   198.7 1917.42
   228.5 1897.63   248.3 1883.41   288.1  1853.4   317.9 1832.59   347.7 1813.83
   367.5 1803.35   397.2 1791.53   416.9 1785.66   436.7 1781.11   446.5 1779.72
   476.1 1778.29  538.66 1773.31   545.2 1772.84   556.81774.022   564.9 1776.75
   604.4 1799.97   643.9 1824.46   703.1 1863.14   743.1 1884.95   773.2    1899
   803.2 1911.24   863.3 1930.06   883.3 1937.71   903.3 1947.58   923.3 1959.85
#Mann= 3 , 0 , 0
       0     .06       0  538.66    .045       0   556.8     .06       0
Bank Sta=538.66,556.8
XS Rating Curve= 0 ,0
Exp/Cntr=0.3,0.1

Type RM Length L Ch R = 1 ,14762.9 ,383.7,389.2,394.5
XS GIS Cut Line= 4
     1822716.591      166802.686      1822728.01      167238.073
     1822833.832       167489.64     1822902.869      167900.323
#Sta/Elev= 30
     9.9 2049.27    29.7 2049.56    39.6 2048.24    69.3  2040.3   118.8 2020.29
   138.6 2010.33   168.3 1993.13     198 1973.86   217.8 1958.99   316.8 1871.37
   336.6 1855.14   366.2 1834.55   395.9 1817.78   425.6 1804.77   455.8 1794.71
   526.5 1777.93   562.6 1772.64   566.9 1772.33   577.61773.011   637.7  1790.7
   708.5 1815.55   748.1 1832.77   777.9 1848.52   827.4 1878.85   886.9 1910.54
   966.3 1955.83   976.2 1957.56   986.1 1955.67  1055.5 1931.03  1124.9 1912.15
#Mann= 3 , 0 , 0
       0     .06       0   562.6    .045       0   577.6     .06       0
Bank Sta=562.6,577.6
XS Rating Curve= 0 ,0
Exp/Cntr=0.3,0.1

Type RM Length L Ch R = 1 ,14373.7 ,263.9,295,326.2
XS GIS Cut Line= 4
     1822664.771      166817.517     1822409.116      167361.813
     1822454.474      167654.579     1822656.524      167992.702
#Sta/Elev= 30
      10 2048.93    30.1 2048.08    50.1 2045.02    70.2 2039.42    80.2 2034.76
   120.3 2012.99   180.4 1977.95   200.4 1965.16   260.6 1922.97   290.7 1904.71
   350.8 1874.89     451 1829.76     461 1824.08   481.1 1807.24   491.1 1800.72
   501.1 1796.66   551.2 1782.09   591.3  1773.1   738.71767.773   739.6 1767.76
   753.71769.023   769.2 1774.32   798.9 1790.24   818.6 1797.92   848.2 1805.95
     868 1807.93   988.5 1804.69  1170.3 1796.41  1251.1 1799.33  1291.5 1804.46
#Mann= 3 , 0 , 0
       0     .06       0   738.7    .045       0   753.7     .06       0
Bank Sta=738.7,753.7
XS Rating Curve= 0 ,0
Exp/Cntr=0.3,0.1

Type RM Length L Ch R = 1 ,14078.6 ,349.1,336.2,323.4
XS GIS Cut Line= 4
      1822596.72      166791.239     1822416.101      167302.196
     1822172.429      167347.083      1821817.11      167622.345
#Sta/Elev= 30
      10 2026.84    30.1 2023.77    70.3 2021.84    90.3 2017.84   100.4 2013.37
   140.5 1989.08   230.8 1950.42     291 1914.59   431.5  1845.4   441.6 1839.04
   451.6 1830.53   471.7 1810.04   481.7  1803.7   531.9 1785.95   571.7 1775.04
   622.61766.477   631.1 1766.09   637.61766.649   700.5 1769.62   799.7 1779.93
   839.7 1788.11   869.6 1798.48   879.6 1804.51   909.6 1828.21  1029.4  1902.6
  1079.4 1937.69  1129.3 1968.03  1169.3 1994.91  1209.2 2017.35  1239.2 2027.14
#Mann= 3 , 0 , 0
       0     .06       0   622.6    .045       0   637.6     .06       0
Bank Sta=622.6,637.6
XS Rating Curve= 0 ,0
Exp/Cntr=0.3,0.1

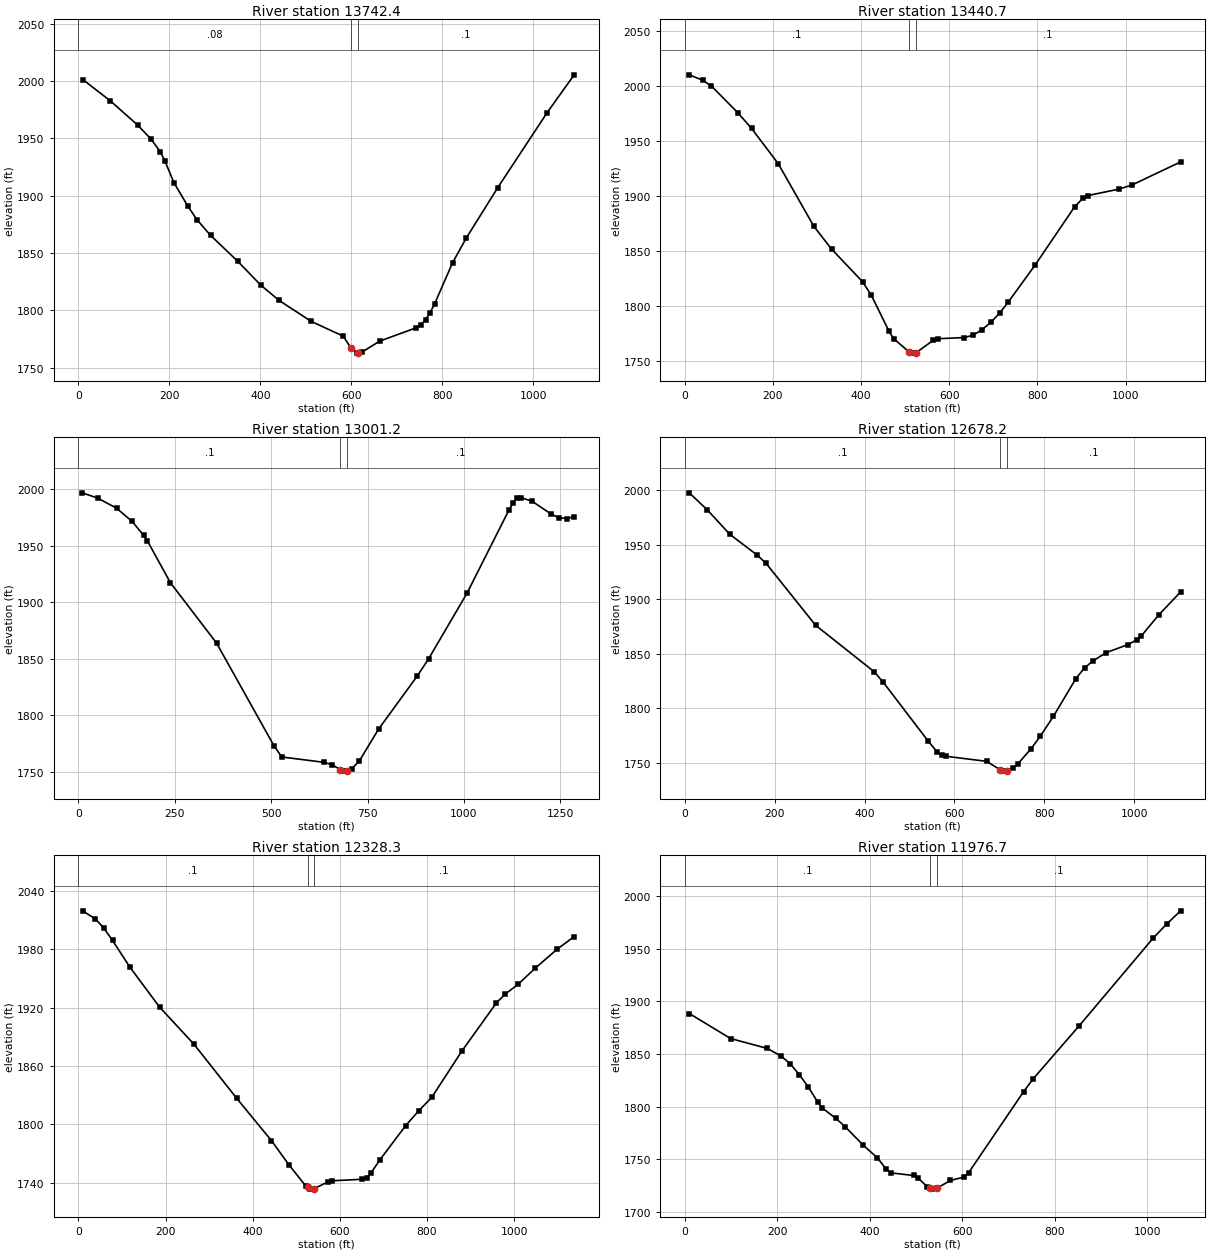
Type RM Length L Ch R = 1 ,13742.4 ,292.5,301.7,310.8
XS GIS Cut Line= 4
     1822454.056      166658.054     1822235.931      166970.085
     1821980.277      167254.603     1821835.956      167547.369
#Sta/Elev= 30
      10 2001.27    70.1  1982.8   130.2 1961.69   160.3 1949.19   180.3 1938.26
   190.4 1930.18   210.4 1911.17   240.4 1891.15   260.5 1879.23   290.5 1865.52
   350.7 1842.73   400.8 1822.16   441.1  1808.8   511.6 1790.52     582 1777.66
   598.61767.675   612.2 1762.84   613.61762.938   622.3 1763.54   662.6 1773.36
   743.1 1785.02   753.2 1787.79   763.2 1792.07   773.1 1798.15     783 1805.87
   822.6 1841.81   852.2 1862.95   921.5    1907  1030.3 1972.53  1089.6 2005.43
#Mann= 3 , 0 , 0
       0     .08       0   598.6    .045       0   613.6      .1       0
Bank Sta=598.6,613.6
XS Rating Curve= 0 ,0
Exp/Cntr=0.3,0.1

Type RM Length L Ch R = 1 ,13440.7 ,463.7,439.5,415.3
XS GIS Cut Line= 4
     1822219.437      166454.653     1822095.733      166817.517
     1821873.067      166908.233     1821679.264       167370.06
#Sta/Elev= 30
    10.1  2010.1    40.4 2005.21    60.5 1999.88   121.1 1975.31   151.3 1961.44
   211.9 1929.37   292.6 1872.47   332.9 1851.69   403.4 1821.95   423.4 1809.52
   463.5 1776.79   473.5 1770.38   508.81758.176   513.6 1757.13   523.51757.189
   563.7 1768.81   573.7 1770.21   633.8  1771.3   653.9 1773.42   673.9 1778.31
   693.9 1785.02     714 1793.44     734 1803.69   794.1 1836.89   884.2 1890.13
   904.3 1898.38   914.3 1900.35   984.4 1906.19  1014.5    1910  1124.7 1930.94
#Mann= 3 , 0 , 0
       0      .1       0   508.8    .045       0   523.5      .1       0
Bank Sta=508.8,523.5
XS Rating Curve= 0 ,0
Exp/Cntr=0.3,0.1

Type RM Length L Ch R = 1 ,13001.2 ,299.6,323,346.4
XS GIS Cut Line= 4
     1821937.004      166220.429     1821596.795      166623.714
     1821588.548      166945.344     1821241.496      167210.199
#Sta/Elev= 30
      10 1996.58    49.8 1991.97    99.6 1982.89   139.4 1971.32   169.2  1959.1
   179.2 1954.02   238.9 1917.08   358.4 1863.85   507.7 1772.87   527.6 1763.18
   638.2 1758.38   658.3  1756.3   679.81751.934   688.5 1750.66   697.31750.756
   708.6 1752.63   728.7 1759.61     779 1787.95   879.1 1834.76   908.9 1850.17
  1008.1 1907.94  1117.2 1981.68  1127.2 1987.72  1137.1 1991.65    1147 1992.44
  1176.8 1989.14  1226.4 1977.77  1246.2 1974.66  1266.1 1973.85  1285.9  1975.5
#Mann= 3 , 0 , 0
       0      .1       0   679.8    .045       0   697.3      .1       0
Bank Sta=679.8,697.3
XS Rating Curve= 0 ,0
Exp/Cntr=0.3,0.1

Type RM Length L Ch R = 1 ,12678.2 ,350.3,349.9,349.5
XS GIS Cut Line= 4
     1821910.178      166157.764     1821485.462      166541.245
      1821209.19      166652.578     1821044.252      166817.517
#Sta/Elev= 30
      10 1997.56    50.2 1981.87   100.4 1959.38   160.6 1940.58   180.7 1932.92
   291.1    1876   421.6 1833.32   441.7 1823.67   542.1 1769.44   562.2  1759.5
   572.2 1756.77   582.2 1755.77   671.5 1751.15   702.41743.291   711.2 1742.18
   717.41742.641   731.1 1745.35     741 1748.81   770.8 1762.82   790.7 1774.03
   820.4 1792.54   870.1 1827.01   889.5 1836.95     909  1843.5   938.1 1851.01
   986.7 1858.37  1006.2 1862.82  1015.9 1866.29  1054.7 1885.56  1103.3 1906.62
#Mann= 3 , 0 , 0
       0      .1       0   702.4    .045       0   717.4      .1       0
Bank Sta=702.4,717.4
XS Rating Curve= 0 ,0
Exp/Cntr=0.3,0.1

Type RM Length L Ch R = 1 ,12328.3 ,357.4,351.6,345.9
XS GIS Cut Line= 4
      1821866.64      166085.229       1821547.2       166182.13
     1821167.955      166330.949     1820771.633      166329.681
#Sta/Elev= 30
     9.8 2019.39    39.3 2011.02    58.9 2001.43    78.5 1988.96   117.8 1961.84
   186.5 1920.44   265.1 1882.46   363.6 1826.64   443.1 1783.31   482.9 1758.59
   522.6 1736.29  525.881735.366   532.5  1733.5  540.121733.815   572.3 1740.88
   582.2 1742.05   651.8 1743.65   661.7 1745.18   671.7 1750.31   691.5 1763.39
   751.1 1798.83   780.8 1813.91   810.6 1827.64   879.9 1875.34   959.2 1924.85
     979 1933.77  1008.7 1943.83  1048.4 1960.59  1097.9 1979.73  1137.5 1992.96
#Mann= 3 , 0 , 0
       0      .1       0  525.88    .045       0  540.12      .1       0
Bank Sta=525.88,540.12
XS Rating Curve= 0 ,0
Exp/Cntr=0.3,0.1

Type RM Length L Ch R = 1 ,11976.7 ,252.8,254.8,256.9
XS GIS Cut Line= 4
     1821691.635      165761.912       1821316.4      165852.628
     1821044.252      166067.047     1820743.239      166223.739
#Sta/Elev= 30
     9.9 1888.42      99 1864.67   178.2 1855.25   207.9 1848.06   227.7 1840.76
   247.5 1830.33   267.3 1818.38   287.1 1804.38     297 1798.63   326.7 1788.68
   346.5 1780.86     386 1763.14   415.7 1751.48   435.5 1740.48   445.4 1736.93
   494.9 1734.42   504.8  1731.8   524.6 1723.56   529.81722.456   534.5 1721.46
   544.81722.271   574.1 1729.68   603.8 1732.97   613.7 1737.14   732.5  1814.2
   752.5 1826.01   852.3  1876.6    1012 1959.87  1041.9 1973.65  1071.9  1986.1
#Mann= 3 , 0 , 0
       0      .1       0   529.8    .045       0   544.8      .1       0
Bank Sta=529.8,544.8
XS Rating Curve= 0 ,0
Exp/Cntr=0.3,0.1

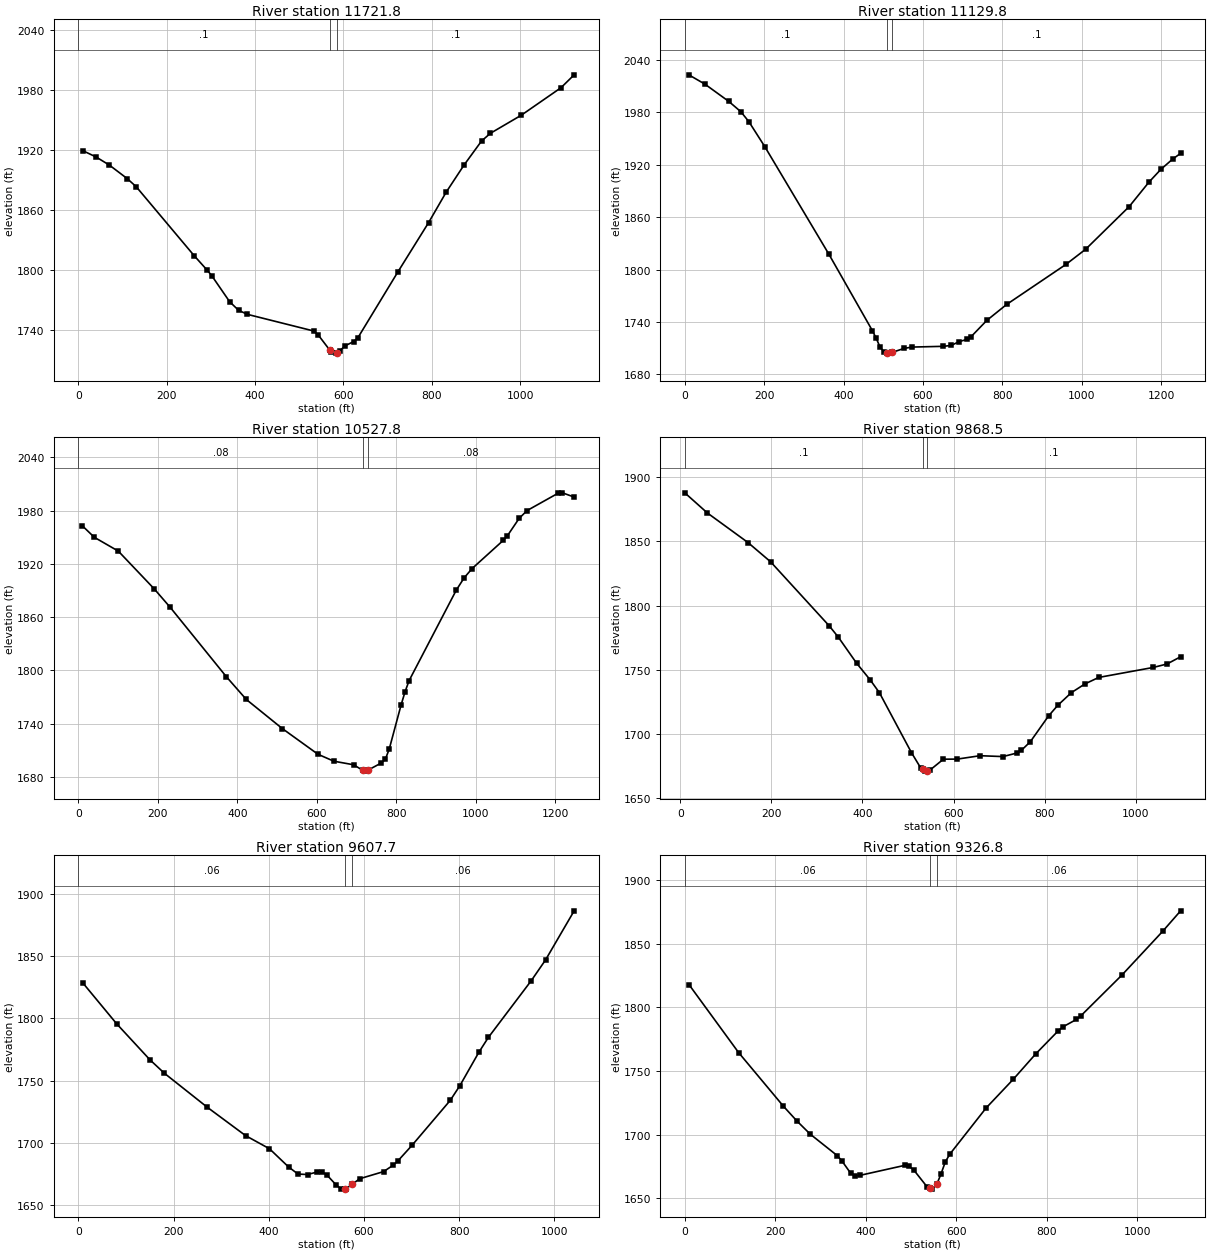
Type RM Length L Ch R = 1 ,11721.8 ,610.6,592.1,573.5
XS GIS Cut Line= 4
     1821576.178      165502.134     1821208.063      165639.486
     1820904.054       165832.01     1820601.361      166043.863
#Sta/Elev= 30
    10.1 1919.02    40.3 1912.66    70.5  1904.5   110.8 1890.98     131 1882.92
   261.9 1814.02   292.2  1799.1   302.2 1793.71   342.5  1767.8   362.7 1759.22
   382.8 1755.15   532.8 1738.49   542.8 1734.62   569.61719.068   572.8  1717.5
   582.8 1716.35   584.61716.811   592.8  1718.9   602.8 1723.45   622.8 1727.84
   632.8  1731.8   722.8 1797.34   792.7 1846.97   832.6 1877.51   872.6  1904.4
   912.5 1928.62   932.5 1936.36  1002.4 1954.46  1092.3 1981.99  1122.2 1994.93
#Mann= 3 , 0 , 0
       0      .1       0   569.6    .045       0   584.6      .1       0
Bank Sta=569.6,584.6
XS Rating Curve= 0 ,0
Exp/Cntr=0.3,0.1

Type RM Length L Ch R = 1 ,11129.8 ,592.7,602,611.4
XS GIS Cut Line= 4
     1820873.679      164761.192     1820821.585      165110.405
     1820772.103      165465.023     1820509.297       165934.49
#Sta/Elev= 30
    10.1 2022.65    50.4 2012.09     111 1992.18   141.2 1980.47   161.4 1969.11
   201.8 1940.34     363 1817.51   472.4 1730.23   482.4 1721.21   492.3  1710.9
   502.3 1705.63   508.21704.882   512.2 1704.37   523.21705.344     552  1709.7
   571.9 1711.29   651.5 1712.15   671.3 1713.18   691.2 1717.56   711.1 1720.06
   721.1 1723.08   760.9 1741.78   810.8 1760.02   960.2 1805.81    1010  1823.2
  1119.6 1871.97  1169.4 1899.93  1199.3 1914.48  1229.2 1926.33  1249.2 1932.84
#Mann= 3 , 0 , 0
       0      .1       0   508.2    .045       0   523.2      .1       0
Bank Sta=508.2,523.2
XS Rating Curve= 0 ,0
Exp/Cntr=0.3,0.1

Type RM Length L Ch R = 1 ,10527.8 ,658.2,659.3,660.3
XS GIS Cut Line= 4
     1820547.473      164720.202     1820351.511      165205.245
     1820161.832       165485.64     1819919.487       165785.28
#Sta/Elev= 30
    10.1 1962.82    40.2 1949.86   100.6 1934.29   191.1 1891.67   231.4 1870.82
   372.2  1792.9   422.5 1767.24   513.1 1734.46   602.8 1705.52   642.6 1697.74
   692.4 1693.71   714.91687.566   722.3 1686.56   729.41687.909   762.1 1695.76
     772 1699.74     782 1711.56   811.9 1761.37   821.8 1776.04   831.8 1788.42
   950.6 1890.44   970.4 1904.27   990.1 1914.57  1069.2 1946.62  1079.1 1951.61
  1108.7 1971.21  1128.5 1979.95  1207.5 1999.74  1217.4 1999.95    1247  1995.2
#Mann= 3 , 0 , 0
       0     .08       0   714.9    .045       0   729.4     .08       0
Bank Sta=714.9,729.4
XS Rating Curve= 0 ,0
Exp/Cntr=0.3,0.1

Type RM Length L Ch R = 1 ,9868.5  ,265,260.8,256.7
XS GIS Cut Line= 4
     1820191.281      164393.356     1820004.855      164697.499
     1819769.497      165010.685      1819641.67      165336.438
#Sta/Elev= 30
     9.9 1887.92    59.5 1872.21   148.6 1849.18   198.2 1834.19     327 1784.21
   346.8 1775.49   386.9  1755.2     417 1742.06   437.1 1732.15   507.4 1685.47
   527.5 1673.65   532.5 1672.32   537.5    1671   542.5 1671.33   547.6 1671.66
   577.7 1680.31   607.9 1680.37   658.1 1683.02   708.3 1682.34   738.5 1685.06
   748.5  1687.1   768.5 1693.94   808.5 1714.02   828.5 1722.21   858.5 1732.17
   888.5    1739   918.5 1744.02  1038.4 1751.82  1068.4 1754.49  1098.4 1760.15
#Mann= 3 , 0 , 0
     9.9      .1       0   532.5    .045       0   542.5      .1       0
Bank Sta=532.5,542.5
XS Rating Curve= 0 ,0
Exp/Cntr=0.3,0.1

Type RM Length L Ch R = 1 ,9607.7  ,270.5,280.9,291.4
XS GIS Cut Line= 4
     1820032.816      164303.317     1819731.431      164598.289
     1819618.145      164820.586     1819383.023      165107.008
#Sta/Elev= 30
      10  1828.1    80.3 1795.66   150.6 1766.62   180.7 1755.91   271.1 1728.55
   351.4 1705.84   401.6  1695.3   441.7  1680.7   461.6 1674.99   481.6 1674.62
   501.6 1676.61   511.5 1676.65   521.5 1674.56   541.5 1666.34   551.5 1663.22
   560.31662.935   561.4  1662.9   575.31666.806   591.4 1671.27   641.3 1676.95
   661.2 1682.01   671.2 1685.45   701.3 1698.12   781.4  1734.1   801.4 1745.74
   841.5 1772.67   861.5 1784.61   951.6 1830.12   981.7 1846.81  1041.8  1886.2
#Mann= 3 , 0 , 0
       0     .06       0   560.3    .045       0   575.3     .06       0
Bank Sta=560.3,575.3
XS Rating Curve= 0 ,0
Exp/Cntr=0.3,0.1

Type RM Length L Ch R = 1 ,9326.8  ,525.3,526.4,527.6
XS GIS Cut Line= 4
       1819980.4      164265.096     1819638.027      164421.587
     1819328.893      164623.837     1819004.933      164756.951
#Sta/Elev= 30
     9.9 1817.66   118.9  1764.6   217.9 1722.47   247.7 1710.88   277.4 1700.45
   336.8 1683.68   346.7 1679.77   366.5 1669.87   376.4 1667.95   386.4 1668.05
   486.3 1675.98   496.3 1675.13   506.2 1672.32   536.2 1658.84   541.91657.962
   546.2  1657.3   556.91660.977   566.1 1668.95   576.1 1678.88   586.1 1684.87
     666 1721.01   725.9  1743.5   775.9 1763.58   825.9 1781.79   835.9 1784.79
   865.9 1790.61   875.9 1793.56     966 1825.34  1056.1  1859.7  1096.1 1875.92
#Mann= 3 , 0 , 0
       0     .06       0   541.9    .045       0   556.9     .06       0
Bank Sta=541.9,556.9
XS Rating Curve= 0 ,0
Exp/Cntr=0.3,0.1

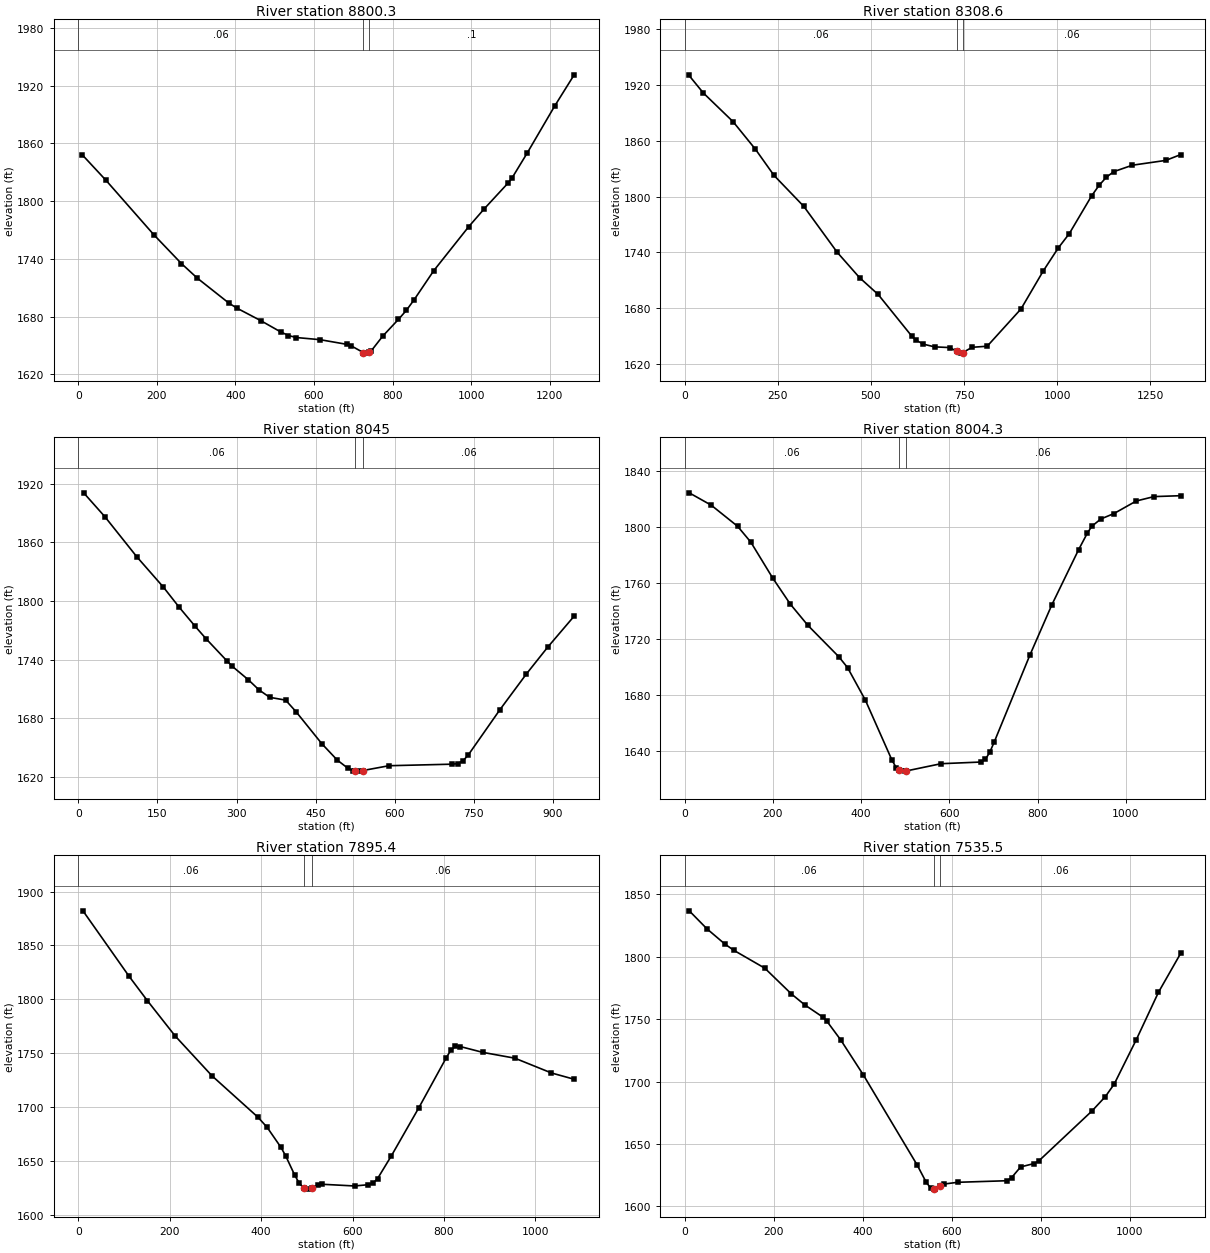
Type RM Length L Ch R = 1 ,8800.3  ,459.2,491.7,524.3
XS GIS Cut Line= 4
     1819858.514      164033.599     1819283.996      164066.878
     1818999.017      164232.109     1818643.915      164274.352
#Sta/Elev= 30
    10.1 1848.11    70.7 1821.51   191.8 1765.27   262.5  1735.1   302.9 1719.96
   383.7 1693.88   403.8 1688.75   464.4 1675.78   514.9 1664.12   535.1 1660.26
   555.3 1658.19   615.4 1655.97   685.3    1651   695.3 1649.45   725.51642.591
   735.2 1641.98   740.51643.062   745.2 1644.03   775.1 1659.66   815.1 1677.08
     835 1686.34     855 1697.45   904.9 1727.65   994.3  1773.6    1034 1792.21
  1093.6 1818.54  1103.6  1823.6  1143.3 1850.26  1212.8 1898.81  1262.5 1931.32
#Mann= 3 , 0 , 0
       0     .06       0   725.5    .045       0   740.5      .1       0
Bank Sta=725.5,740.5
XS Rating Curve= 0 ,0
Exp/Cntr=0.3,0.1

Type RM Length L Ch R = 1 ,8308.6  ,289.5,263.6,237.7
XS GIS Cut Line= 4
     1819904.762      163900.016     1819386.622       163935.22
     1819205.006       163597.12      1818776.35      163592.973
#Sta/Elev= 30
      10 1930.59    49.9 1911.08   129.8 1880.26   189.8  1850.7   239.7 1822.65
   319.6 1789.46   409.5 1740.11   469.4 1712.97   519.3 1694.96   610.2 1649.97
   620.3 1646.09   640.5 1641.66   670.8 1638.72   711.2 1637.97   731.81633.767
   741.5    1632   746.81632.658   771.8 1638.26   812.2 1639.39   903.1 1679.43
   962.9 1720.22  1002.8 1744.64  1032.7 1760.18  1092.5  1800.6  1112.5 1811.86
  1132.4 1820.78  1152.4 1826.73  1202.2 1833.62  1291.9 1838.77  1331.8 1844.98
#Mann= 3 , 0 , 0
       0     .06       0   731.8    .045       0   746.8     .06       0
Bank Sta=731.8,746.8
XS Rating Curve= 0 ,0
Exp/Cntr=0.3,0.1

Type RM Length L Ch R = 1 ,8045    ,41.7,40.7,39.7
XS GIS Cut Line= 4
      1819917.76      163779.678      1819597.29      163551.965
     1819394.453       163586.78      1819053.87      163564.075
#Sta/Elev= 30
    10.1 1910.54    50.4 1886.08   110.9 1845.12   161.3 1814.08   191.5 1793.35
   221.8 1773.83   241.9 1761.46   282.2 1738.41   292.3 1732.91   322.6 1719.23
   342.7 1708.93   362.9 1701.36   393.1  1698.5   412.7 1686.76   461.7 1653.95
   491.1 1637.14   510.7 1629.02   520.5 1626.51   524.81626.232   530.3 1625.87
   539.8 1626.49   589.1  1631.4   709.4 1632.99   719.4 1633.55   729.4 1636.34
   739.5 1642.41   799.7 1688.85   849.9 1725.39   890.1 1752.65   940.3 1784.42
#Mann= 3 , 0 , 0
       0     .06       0   524.8    .045       0   539.8     .06       0
Bank Sta=524.8,539.8
XS Rating Curve= 0 ,0
Exp/Cntr=0.3,0.1

Type RM Length L Ch R = 1 ,8004.3  ,105.4,108.9,112.4
XS GIS Cut Line= 4
     1819930.217      163610.775     1819576.098      163506.554
     1819350.556      163561.047     1818827.279      163553.063
#Sta/Elev= 30
      10 1824.12    59.9 1815.32   119.7 1800.27   149.7 1788.96   199.5 1763.28
   239.4 1744.69   279.3 1729.54   349.2 1707.24   369.1 1699.47   409.5 1676.27
     470 1633.33   480.1 1627.81   486.6 1626.42   500.3 1625.62   501.61625.698
     581 1630.91   671.6 1632.11   681.7    1634   691.7 1639.12   701.8 1646.42
   782.3 1708.13   832.6 1744.35     893 1783.49   913.2 1795.53   923.2 1800.29
   943.4 1805.44   973.5 1809.37  1023.9 1818.29  1064.1 1821.43  1124.5 1822.07
#Mann= 3 , 0 , 0
       0     .06       0   486.6    .045       0   501.6     .06       0
Bank Sta=486.6,501.6
XS Rating Curve= 0 ,0
Exp/Cntr=0.3,0.1

Type RM Length L Ch R = 1 ,7895.4  ,358.5,359.9,361.2
XS GIS Cut Line= 4
     1819937.462      163474.378     1819578.721      163420.773
     1819186.993      163445.513      1818861.24      163396.032
#Sta/Elev= 30
    10.1 1882.19   110.8 1821.48   151.1 1798.68   211.6 1766.02   292.2 1728.96
   392.9 1690.43     413 1681.03   443.2 1662.45   453.3 1654.72   473.4 1636.58
   483.5 1628.84  494.181624.428   503.6 1623.59   511.21624.848   523.8 1627.42
   533.8  1628.1   604.3 1626.52   634.5 1627.71   644.5 1629.11   654.6 1633.35
   684.8 1654.51   745.2 1699.43   805.2 1745.89   815.1  1752.8   825.1 1756.18
   835.1 1756.12     885 1750.65   954.9 1745.27  1034.8 1731.56  1084.7 1725.69
#Mann= 3 , 0 , 0
       0     .06       0  494.18    .045       0   511.2     .06       0
Bank Sta=494.18,511.2
XS Rating Curve= 0 ,0
Exp/Cntr=0.3,0.1

Type RM Length L Ch R = 1 ,7535.5  ,225.7,230.3,234.8
XS GIS Cut Line= 4
     1819997.788      163133.287     1819703.429      163077.415
     1819167.361      163073.389     1818922.915      162939.541
#Sta/Elev= 30
      10 1836.77    49.9 1822.32    89.9 1810.21   109.9 1805.22   179.8 1790.84
   239.7 1770.18   269.7 1761.44   309.7 1751.81   319.8 1748.16   350.2 1733.52
   400.8 1705.65   522.1 1633.33   542.4 1619.54   552.5 1614.74   559.21614.189
   562.6 1613.91   574.21616.234   582.8 1617.98   613.2 1619.38   724.4 1620.64
   734.5 1623.14   754.8 1631.68   785.1  1634.4   795.2 1636.35   915.3 1676.54
   945.2 1687.99   965.1 1698.01  1014.9 1733.69  1064.6 1771.54  1114.4 1802.66
#Mann= 3 , 0 , 0
       0     .06       0   559.2    .045       0   574.2     .06       0
Bank Sta=559.2,574.2
XS Rating Curve= 0 ,0
Exp/Cntr=0.3,0.1

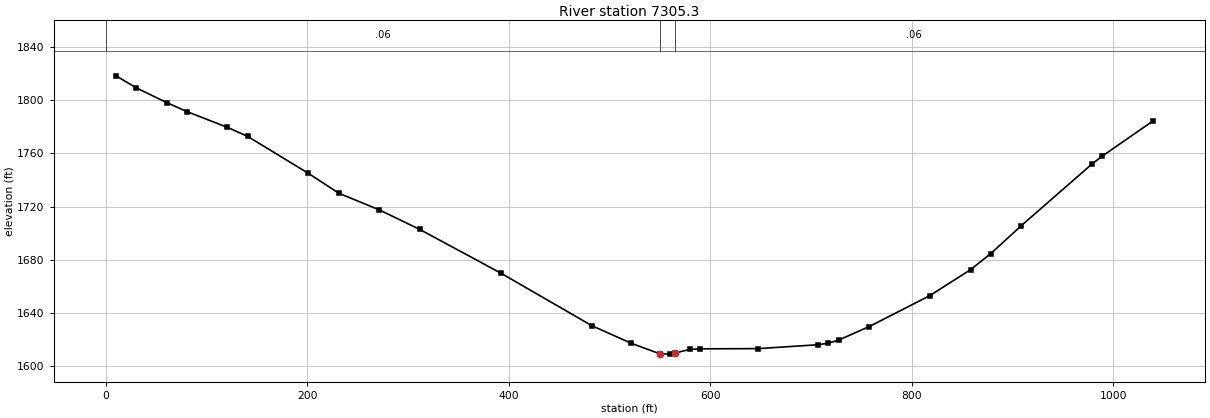
Type RM Length L Ch R = 1 ,7305.3  ,301.6,321.6,341.7
XS GIS Cut Line= 4
     1819965.014      163117.397     1819552.481      162867.313
     1819372.933      162824.563     1819004.776      162767.692
#Sta/Elev= 30
    10.1 1818.29    30.2 1809.24    60.3  1798.2    80.4 1791.41   120.6 1779.55
   140.7 1772.78     201 1744.99   231.2 1730.04   271.4 1717.52   311.6  1702.8
     392    1670   482.4 1630.47   521.3 1617.29   549.91609.323   560.1 1609.08
   564.91609.992   579.6 1612.58   589.3 1613.05   647.6 1613.23   707.3 1616.16
   717.3 1617.35   727.4 1619.64   757.6 1629.75     818  1653.1   858.3 1672.56
   878.4 1684.65   908.6 1705.57   979.1 1752.17   989.2    1758  1039.5 1784.41
#Mann= 3 , 0 , 0
       0     .06       0   549.9    .045       0   564.9     .06       0
Bank Sta=549.9,564.9
XS Rating Curve= 0 ,0
Exp/Cntr=0.3,0.1