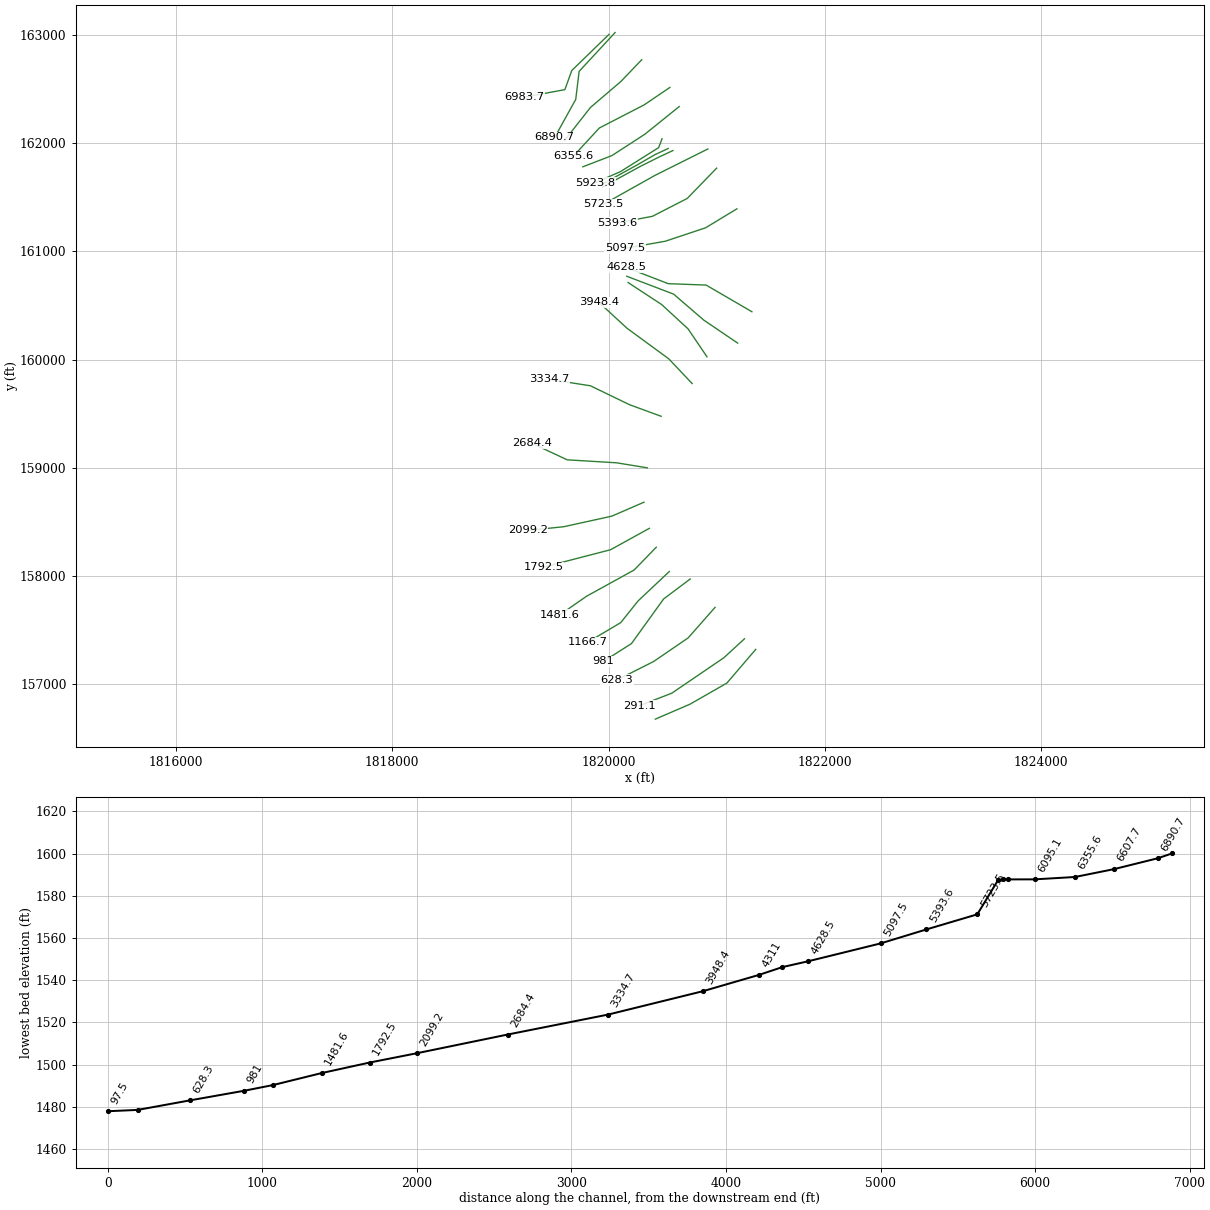
HEC-RAS study Laurel Branch B.prj: Laurel Branch B

--- Laurel Branch B.g01 (geometry) --- (continued)

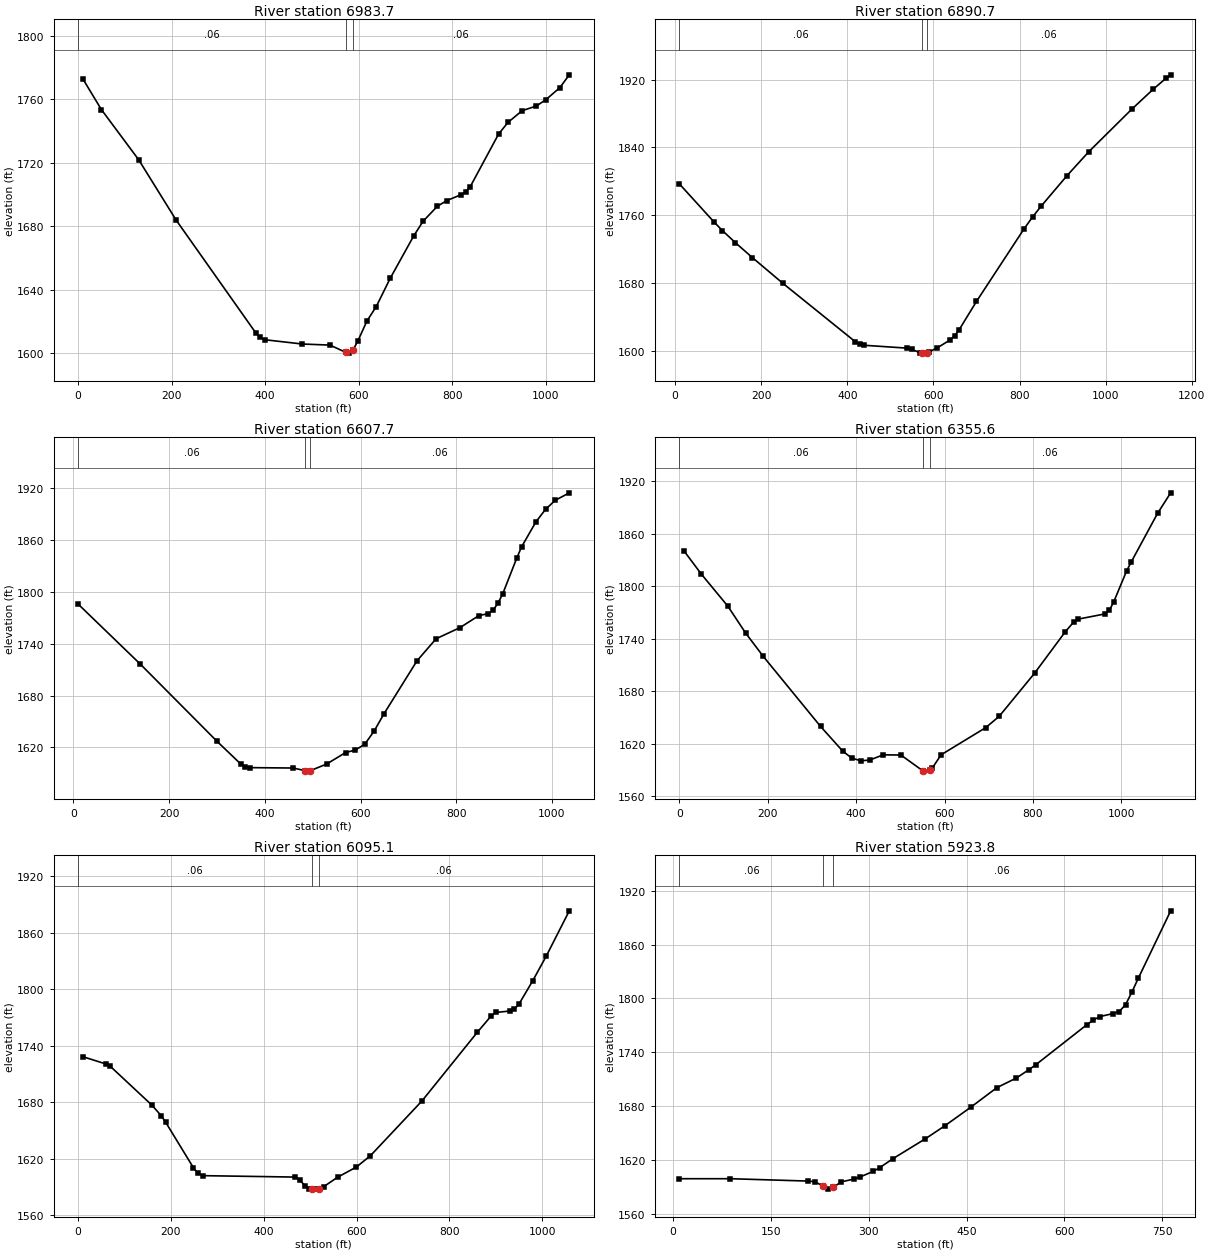
Type RM Length L Ch R = 1 ,6983.7  ,88.3,93,97.6
XS GIS Cut Line= 4
     1820003.212      163006.719     1819659.459      162672.676
      1819595.37      162495.944       1819218.6      162426.028
#Sta/Elev= 30
      10 1772.77    49.9 1753.35   129.8  1721.7   209.7 1683.81   379.5 1613.03
   389.5 1609.99   399.4 1608.52   479.3 1605.83   538.7 1605.14   572.51600.579
   578.3 1600.09   587.51601.856   598.1 1607.63   617.8 1620.36   637.6 1629.36
   667.3 1647.08   717.7 1673.84   737.9 1683.13   768.2 1692.49   788.3 1696.09
   818.6 1699.75   828.7 1701.65   838.7 1704.88   899.3 1737.98   919.4 1745.33
   949.7  1752.7   979.9 1755.62  1000.1 1759.54  1030.3 1767.19  1050.5 1775.26
#Mann= 3 , 0 , 0
       0     .06       0   572.5    .045       0   587.5     .06       0
Bank Sta=572.5,587.5
XS Rating Curve= 0 ,0
Exp/Cntr=0.3,0.1

Type RM Length L Ch R = 1 ,6890.7  ,297.9,283,268
XS GIS Cut Line= 4
     1820059.562      163023.445     1819727.433      162664.907
     1819695.881      162405.417     1819501.526      162054.693
#Sta/Elev= 30
      10    1797    89.8  1752.5   109.7 1742.13   139.6 1728.02   179.5 1710.26
   249.4 1680.33   418.9 1611.03   428.9 1608.24   438.9 1607.04     539 1603.65
   549.1 1602.35   569.2 1598.12   574.2 1597.95   579.2 1597.78   584.2  1598.4
   589.3 1599.04   609.4 1604.11   639.5 1613.63   649.6 1618.48   659.6 1625.24
   699.9 1658.63   810.3 1744.04   830.3 1758.21   850.4 1771.04   910.5 1806.97
   960.6 1834.88  1060.9 1885.19    1111 1908.86  1141.1 1921.92  1151.1  1925.6
#Mann= 3 , 0 , 0
      10     .06       0   574.2    .045       0   584.2     .06       0
Bank Sta=574.2,584.2
XS Rating Curve= 0 ,0
Exp/Cntr=0.3,0.1

Type RM Length L Ch R = 1 ,6607.7  ,257.1,252.1,247.1
XS GIS Cut Line= 4
     1820306.153      162772.405      1820112.35      162570.355
     1819831.955      162331.195     1819592.795      162026.059
#Sta/Elev= 30
      10 1785.93     140 1716.43   299.9 1627.29   349.7 1600.93   359.7 1597.82
   369.6 1596.68   459.3 1596.23   484.1 1593.22   489.1 1592.64   494.1 1592.99
     529 1600.76   568.8 1614.12   588.7 1616.97   608.7 1623.61   628.6  1639.1
   648.5  1658.5   718.1 1720.35   757.9 1745.78   807.6 1758.61   847.3 1772.59
   867.2  1774.9   877.1 1778.79   887.1 1786.86     897 1797.63   926.9  1839.8
   936.8  1852.4   966.6 1881.18   986.5 1895.44  1006.4 1905.82  1036.2 1914.64
#Mann= 3 , 0 , 0
      10     .06       0   484.1    .045       0   494.1     .06       0
Bank Sta=484.1,494.1
XS Rating Curve= 0 ,0
Exp/Cntr=0.3,0.1

Type RM Length L Ch R = 1 ,6355.6  ,258.5,260.5,262.5
XS GIS Cut Line= 4
     1820566.916       162516.64     1820327.699      162354.564
     1819914.424      162141.516     1819671.877      161878.663
#Sta/Elev= 30
      10  1840.5    49.8 1813.66   109.6 1777.15   149.5 1746.72   189.3 1720.12
   319.3 1639.93   369.8 1611.56     390 1603.82   410.2 1600.75   430.5 1601.52
   460.8 1607.54   501.2 1607.28     5511589.157   551.8 1588.92     5661590.336
     572 1592.38   592.2  1607.6   693.3 1638.66   723.6 1651.53   803.6 1700.72
   873.1 1748.05     893 1759.68   902.9 1762.54   962.5 1768.37   972.5 1772.33
   982.4 1781.75  1012.2  1817.9  1022.2 1827.58  1081.8 1883.13  1111.6 1906.67
#Mann= 3 , 0 , 0
       0     .06       0     551    .045       0     566     .06       0
Bank Sta=551,566
XS Rating Curve= 0 ,0
Exp/Cntr=0.3,0.1

Type RM Length L Ch R = 1 ,6095.1  ,171.6,171.3,171
XS GIS Cut Line= 4
     1820652.523      162339.442     1820335.017      162083.787
     1820029.881      161885.861     1819761.856      161782.775
#Sta/Elev= 30
     9.9 1728.45    59.7  1720.7    69.6 1718.08   159.1 1676.93     179 1665.82
   188.9 1658.63   248.6 1610.45   258.5 1604.53   268.4  1602.1   468.3 1600.59
   478.4 1597.17   488.5 1591.51   498.6 1588.12   503.81587.957   508.7  1587.8
   518.8 1588.01   528.9 1590.26   559.2 1600.44   599.6 1611.22   629.9 1623.25
     741 1681.41   860.5 1754.45   890.2 1771.67   900.1 1775.36   929.8 1776.85
   939.7 1778.76   949.6  1783.9   979.3 1808.64    1009 1835.32  1058.5 1883.24
#Mann= 3 , 0 , 0
       0     .06       0   503.8    .045       0   518.8     .06       0
Bank Sta=503.8,518.8
XS Rating Curve= 0 ,0
Exp/Cntr=0.3,0.1

Type RM Length L Ch R = 1 ,5923.8  ,34.5,33.7,32.9
XS GIS Cut Line= 4
     1820493.604      162042.204     1820462.844      161960.083
     1820108.227      161737.417      1819873.19       161634.33
#Sta/Elev= 30
     9.7 1599.37    87.7 1599.38   207.3 1596.73   217.3 1596.02   230.51590.996
   237.2 1587.78   245.51590.118   247.2 1590.41   257.2 1595.76   277.1 1598.95
   287.1 1601.44     307 1607.56     317 1611.77   336.9 1621.58   386.8 1643.79
   416.7 1658.26   456.6 1678.99   496.5 1700.72   526.2 1711.34   545.9 1720.83
   555.8 1725.96   634.7 1770.88   644.6 1776.06   654.5 1779.81   674.2 1783.11
   684.1 1785.39     694  1793.1   703.8 1807.41   713.7 1822.87   763.1 1897.52
#Mann= 3 , 0 , 0
     9.7     .06       0   230.5    .045       0   245.5     .06       0
Bank Sta=230.5,245.5
XS Rating Curve= 0 ,0
Exp/Cntr=0.3,0.1

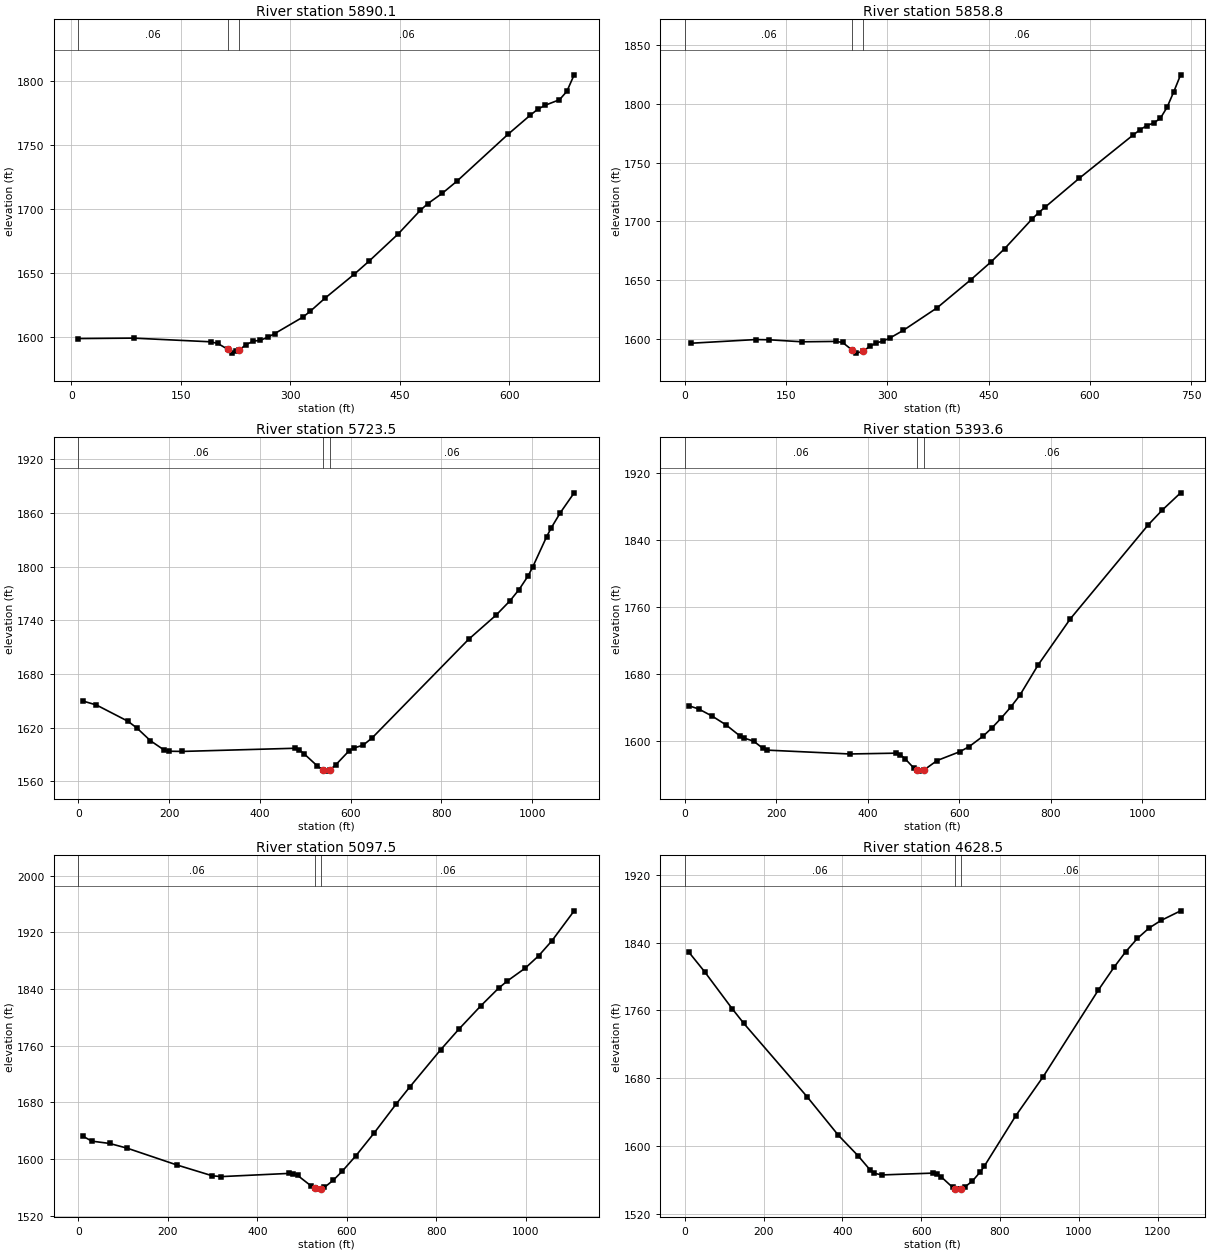
Type RM Length L Ch R = 1 ,5890.1  ,32.5,31.3,30.2
XS GIS Cut Line= 4
     1820550.381      161951.781     1820430.476      161895.832
     1820261.513      161798.727     1819944.949      161623.937
#Sta/Elev= 30
     9.5 1599.12    85.1 1599.46   190.8 1596.59   200.5 1595.29   214.71590.629
     220 1587.76     225 1589.61   229.71590.129   239.5 1594.46   249.2 1597.05
     259 1597.83   268.7 1600.04   278.5 1602.98   317.5 1615.97   327.2 1620.39
   347.3 1630.54   387.5  1649.3   407.6 1659.39   447.7 1680.71   477.9 1699.05
   487.9 1704.18     508 1712.38   528.1 1721.82   598.4 1758.54   628.5 1773.25
   638.6 1777.83   648.6 1780.98   668.7 1785.38   678.8 1791.94   688.8 1804.81
#Mann= 3 , 0 , 0
     9.5     .06       0   214.7    .045       0   229.7     .06       0
Bank Sta=214.7,229.7
XS Rating Curve= 0 ,0
Exp/Cntr=0.3,0.1

Type RM Length L Ch R = 1 ,5858.8  ,135.3,135.3,136.3
XS GIS Cut Line= 4
     1820594.541      161932.855     1820473.203      161876.411
     1820294.529      161787.074     1819943.007      161594.806
#Sta/Elev= 30
     9.6 1596.01   105.1 1599.13   124.3 1598.96   173.8 1597.22   223.7 1597.55
   233.7 1596.67   247.81590.193   253.7 1587.56  264.141589.074   273.7  1593.3
   283.6 1596.23   293.6 1597.92   303.6 1600.39   323.6 1606.98   373.7 1626.23
   423.7 1650.21   453.8  1665.5   473.8 1676.73   513.9 1701.71   523.9 1707.29
   533.9  1712.2     584 1736.59   664.1 1773.63   674.2 1778.05   684.2 1781.61
   694.2 1783.73   704.2 1787.74   714.2 1797.17   724.2 1810.53   734.3 1824.89
#Mann= 3 , 0 , 0
       0     .06       0   247.8    .045       0  264.14     .06       0
Bank Sta=247.8,264.14
XS Rating Curve= 0 ,0
Exp/Cntr=0.3,0.1

Type RM Length L Ch R = 1 ,5723.5  ,329.7,329.9,329.2
XS GIS Cut Line= 3
     1820917.508      161947.481     1820428.544      161703.259
     1819952.438      161436.181
#Sta/Elev= 30
     9.9 1649.65    39.7 1645.23   109.3 1627.01   129.2 1619.38     159 1605.18
   188.8 1594.93   198.7  1593.5   228.6 1593.25     477  1596.8   486.9 1594.77
   496.9 1590.86   526.7 1576.95   539.11572.375   546.6 1571.23   554.11572.521
   566.8 1578.06   597.1 1594.24   607.2  1597.1   627.4  1600.2   647.7 1608.55
   859.9 1718.61   920.6 1745.76   950.9 1761.58   971.2 1774.33   991.4 1789.84
  1001.5 1799.87  1031.8 1833.34  1041.9 1843.17  1062.1 1860.29  1092.5 1882.46
#Mann= 3 , 0 , 0
       0     .06       0   539.1    .045       0   554.1     .06       0
Bank Sta=539.1,554.1
XS Rating Curve= 0 ,0
Exp/Cntr=0.3,0.1

Type RM Length L Ch R = 1 ,5393.6  ,299.1,296.1,293
XS GIS Cut Line= 4
     1820998.894      161770.404     1820726.745      161490.009
     1820405.116      161325.071     1820079.363      161263.219
#Sta/Elev= 30
      10 1641.95    30.1 1638.39    60.1 1629.71    90.2 1619.28   120.2 1606.25
   130.3 1603.41   150.3 1599.95   170.3 1591.46   180.3 1589.14   360.7 1584.56
     461 1585.53   471.1 1583.57   481.1 1579.09   501.2 1567.42   507.81565.212
   511.2 1564.07   522.81565.402   551.4  1576.7   601.6 1587.38   621.7 1593.43
   651.8 1605.75   671.9 1615.99     692 1627.65     712 1640.28   732.1 1654.47
   772.3 1690.92   842.6 1745.92  1013.4 1858.53  1043.6  1875.9  1083.8 1896.53
#Mann= 3 , 0 , 0
       0     .06       0   507.8    .045       0   522.8     .06       0
Bank Sta=507.8,522.8
XS Rating Curve= 0 ,0
Exp/Cntr=0.3,0.1

Type RM Length L Ch R = 1 ,5097.5  ,476.2,469,461.8
XS GIS Cut Line= 4
     1821186.093      161394.089      1820895.65      161218.279
     1820524.539      161094.575     1820152.871      161029.263
#Sta/Elev= 30
      10 1632.25      30 1625.21    69.9 1621.94   109.8 1615.13   219.7 1591.67
   299.6 1576.24   319.5 1575.14   469.9 1579.62   479.9 1579.19     490 1576.83
   520.1 1562.02   527.81559.032   540.1 1557.45   542.81558.147   550.1 1560.03
   570.2 1570.25   590.3  1583.1   620.4 1604.65   660.5 1636.22   710.6 1677.87
   740.6 1701.56   810.1 1754.48   849.9  1782.9   899.5 1816.23   939.2 1841.11
   959.1 1851.48   998.8 1869.47  1028.6 1886.76  1058.4 1908.03  1108.1 1950.34
#Mann= 3 , 0 , 0
       0     .06       0   527.8    .045       0   542.8     .06       0
Bank Sta=527.8,542.8
XS Rating Curve= 0 ,0
Exp/Cntr=0.3,0.1

Type RM Length L Ch R = 1 ,4628.5  ,180.2,166.3,152.4
XS GIS Cut Line= 4
     1821324.647      160442.651     1820901.399      160689.199
     1820551.601      160702.075     1820161.265      160852.613
#Sta/Elev= 30
      10 1828.85      50 1805.78     120  1762.1   149.9 1744.53   309.9 1658.28
   389.9 1612.45   439.8 1588.29   469.8 1571.89   479.8 1567.84   499.8 1565.73
   629.8 1567.91   639.8 1566.64   649.8 1563.85   679.8 1550.99   686.3 1549.69
   689.8 1548.99  699.971549.431   709.8  1551.2   729.8 1558.48   749.8  1569.3
   759.8 1575.89   839.9 1635.61   909.6 1681.84    1049 1783.66  1088.9 1810.69
  1118.8 1829.18  1148.6 1844.99  1178.5 1857.29  1208.4 1866.09  1258.2 1877.49
#Mann= 3 , 0 , 0
       0     .06       0   686.3    .045       0  699.97     .06       0
Bank Sta=686.3,699.97
XS Rating Curve= 0 ,0
Exp/Cntr=0.3,0.1

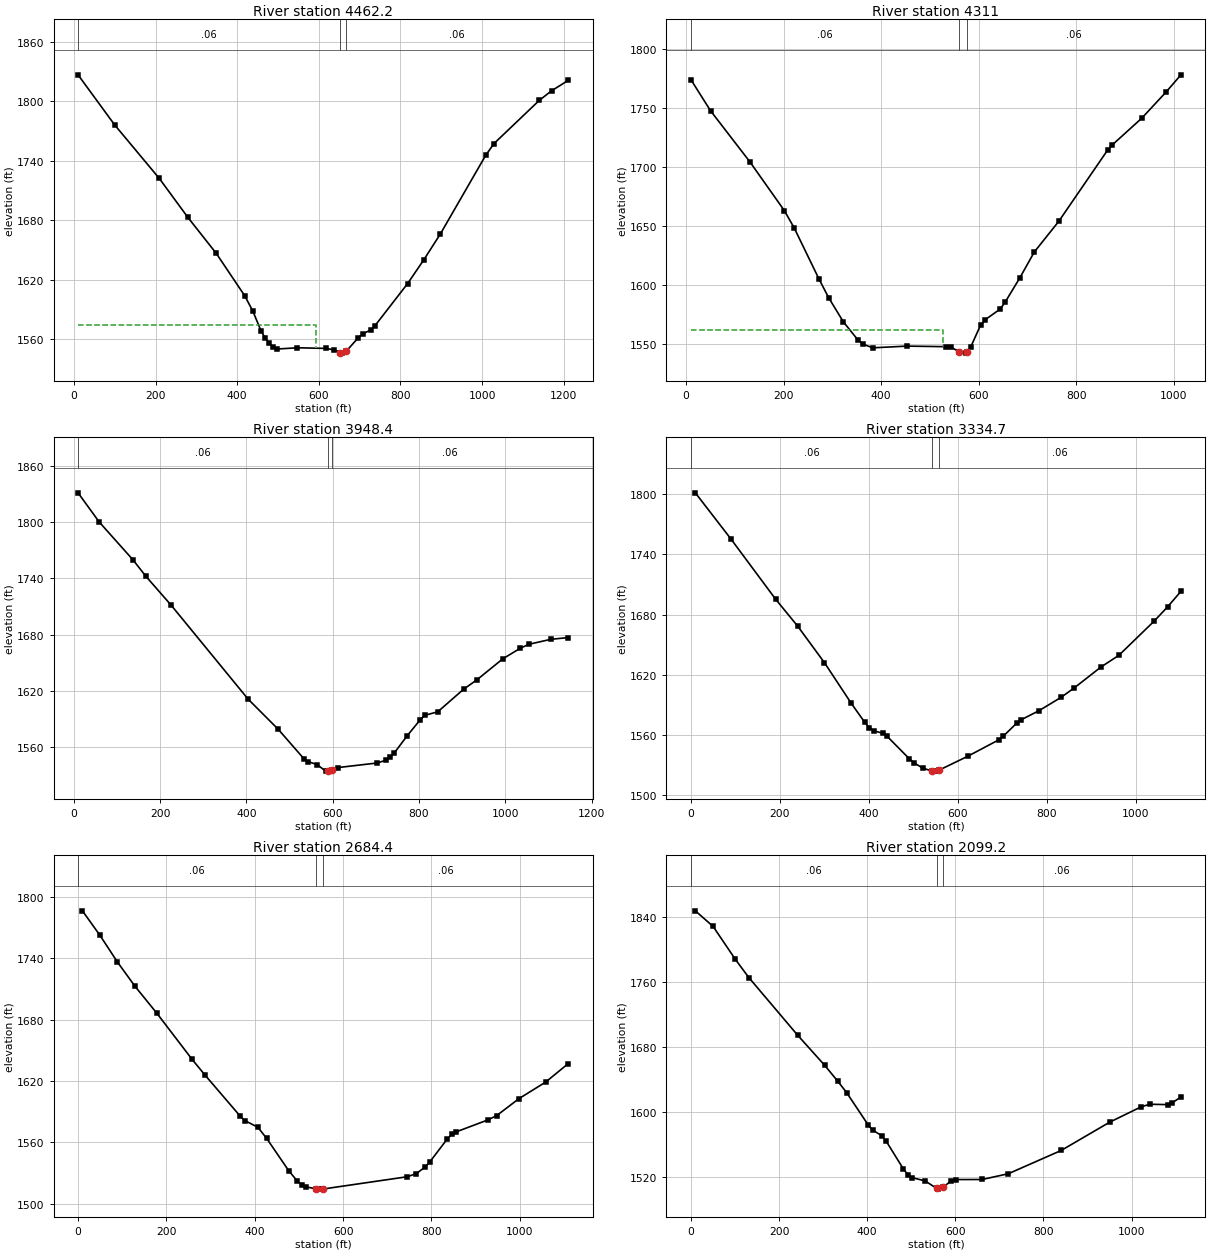
Type RM Length L Ch R = 1 ,4462.2  ,152,151.2,150.5
XS GIS Cut Line= 4
     1821193.255      160152.699     1820879.939      160365.153
     1820600.959      160605.505     1820167.466      160770.747
#Sta/Elev= 30
      10 1826.72    99.6 1776.31   209.2 1722.25   278.9 1683.15   348.7 1646.76
   418.4 1604.05   438.3 1588.56   458.2 1568.84   468.1 1561.72   478.1 1556.52
     488 1552.41     498 1550.38   547.7 1551.64   617.4    1551   637.3 1549.54
   652.51546.757   657.2 1546.24   667.51548.295     697 1561.94     707  1565.5
   726.9 1569.58   736.8 1573.47   817.4 1616.26   857.7  1640.6   898.1 1666.57
    1009 1745.67  1029.2 1757.46  1140.1 1800.95  1170.4 1810.68  1210.7 1821.01
#Mann= 3 , 0 , 0
      10     .06       0   652.5    .045       0   667.5     .06       0
#XS Ineff= 2 , 0
          591.87 1574.53
Permanent Ineff=
       F       F
Bank Sta=652.5,667.5
XS Rating Curve= 0 ,0
Exp/Cntr=0.3,0.1

Type RM Length L Ch R = 1 ,4311    ,360.2,362.5,364.9
XS GIS Cut Line= 4
     1820909.181      160026.228     1820733.908      160284.863
     1820490.235      160509.298     1820180.301      160712.358
#Sta/Elev= 30
    10.1 1773.87    50.4  1747.5     131 1704.32   201.6 1663.08   221.7 1648.51
   272.1 1605.64   292.3  1589.5   322.5 1569.01   352.6  1553.6   362.6 1550.19
   382.7 1547.03     453 1548.49   533.3    1548   543.3 1547.53   559.91543.685
   573.4 1542.55   574.91543.318   583.5 1547.73   603.6 1566.17   613.6 1570.93
   643.7 1579.76   653.7 1585.44   683.8 1605.97   713.8 1628.09   763.9    1654
     864 1714.25     874  1718.8   934.1 1741.28   984.2 1763.53  1014.2  1777.9
#Mann= 3 , 0 , 0
    10.1     .06       0   559.9    .045       0   574.9     .06       0
#XS Ineff= 2 , 0
          527.17 1562.43
Permanent Ineff=
       F       F
Bank Sta=559.9,574.9
XS Rating Curve= 0 ,0
Exp/Cntr=0.3,0.1

Type RM Length L Ch R = 1 ,3948.4  ,610.1,613.8,617.4
XS GIS Cut Line= 4
     1820772.103      159778.774     1820556.497      160006.991
     1820170.079      160290.083     1819910.848      160528.798
#Sta/Elev= 30
     9.8 1831.25    58.9 1800.17   137.4  1759.7   166.8 1742.47   225.7 1711.49
   403.8 1611.58   473.6 1579.43   533.5 1547.88   543.5 1544.86   563.4 1541.88
   583.4 1534.97   588.4  1534.9   593.4 1534.83   598.4  1535.9   613.3 1538.69
   703.2  1543.5   723.1 1546.44   733.1 1549.52   743.1 1554.45     773 1572.77
     803 1589.65   813.1 1594.27   843.3 1597.97   903.7 1622.22   933.9    1632
   994.3  1654.5  1034.6  1665.7  1054.8 1669.95  1105.1 1675.18  1145.4 1677.09
#Mann= 3 , 0 , 0
     9.8     .06       0   588.4    .045       0   598.4     .06       0
Bank Sta=588.4,598.4
XS Rating Curve= 0 ,0
Exp/Cntr=0.3,0.1

Type RM Length L Ch R = 1 ,3334.7  ,642.5,650.3,658.1
XS GIS Cut Line= 4
     1820485.422      159476.129     1820194.081      159582.959
     1819831.955      159758.157     1819447.813      159817.974
#Sta/Elev= 30
      10 1801.41    90.1 1755.32   190.2 1695.43   240.2 1668.29   300.3  1631.9
   360.6  1591.3   390.8 1572.43   400.8 1567.09   410.9 1564.05     431 1561.55
   441.1 1558.47   491.3 1535.92   501.4 1532.05   521.5 1526.67   542.61523.822
   551.7 1523.75   557.61524.684   622.1 1538.53   692.5 1555.07   702.5 1558.75
   732.5 1571.68   742.5 1575.02   782.4 1584.05   832.2  1597.4   862.1 1606.92
   921.9 1627.69   961.8 1639.24  1041.6 1673.55  1071.5  1687.7  1101.4 1703.09
#Mann= 3 , 0 , 0
       0     .06       0   542.6    .045       0   557.6     .06       0
Bank Sta=542.6,557.6
XS Rating Curve= 0 ,0
Exp/Cntr=0.3,0.1

Type RM Length L Ch R = 1 ,2684.4  ,579.5,585.2,590.9
XS GIS Cut Line= 4
     1820358.099      158999.536     1820074.103      159046.122
     1819617.535      159073.663     1819287.661      159227.649
#Sta/Elev= 30
     9.9 1786.47    49.6 1762.51    89.3  1736.3     129 1712.63   178.6  1686.2
     258 1641.28   287.8 1625.62   367.3 1585.54   377.3  1581.4   407.1 1574.76
     427 1563.87   476.7 1532.44   496.6 1522.02   506.5 1518.55   516.5 1516.45
     5391514.579   546.3 1514.29     5541514.362   745.2 1526.41   765.4 1529.41
   785.6 1535.86   795.8 1540.68   836.2 1563.57   846.3 1567.76   856.4 1570.36
   927.2  1581.9   947.4 1586.12     998 1602.78  1058.7 1619.05  1109.2 1636.95
#Mann= 3 , 0 , 0
       0     .06       0     539    .045       0     554     .06       0
Bank Sta=539,554
XS Rating Curve= 0 ,0
Exp/Cntr=0.3,0.1

Type RM Length L Ch R = 1 ,2099.2  ,305.9,306.7,307.4
XS GIS Cut Line= 4
      1820326.77      158681.934     1820030.073       158552.97
     1819584.548      158455.144     1819254.038       158420.97
#Sta/Elev= 30
    10.1 1847.42    50.5 1828.19   101.1 1787.63   131.4 1765.48   242.6 1694.37
   303.3 1657.79   333.4 1638.01   353.3 1624.17   402.8 1583.93   412.8 1577.87
   432.6 1571.29   442.5 1564.97   482.2 1530.23   492.1 1523.43     502 1519.63
   531.8 1515.48   557.71506.336   561.5 1505.47   572.71507.884   591.2 1516.01
   601.2 1517.22   660.7 1517.31   720.2 1524.37   840.1 1552.94   950.8  1587.9
  1021.3 1606.49  1041.4 1609.79  1081.7 1609.29  1091.8 1611.36  1111.9 1618.72
#Mann= 3 , 0 , 0
       0     .06       0   557.7    .045       0   572.7     .06       0
Bank Sta=557.7,572.7
XS Rating Curve= 0 ,0
Exp/Cntr=0.3,0.1

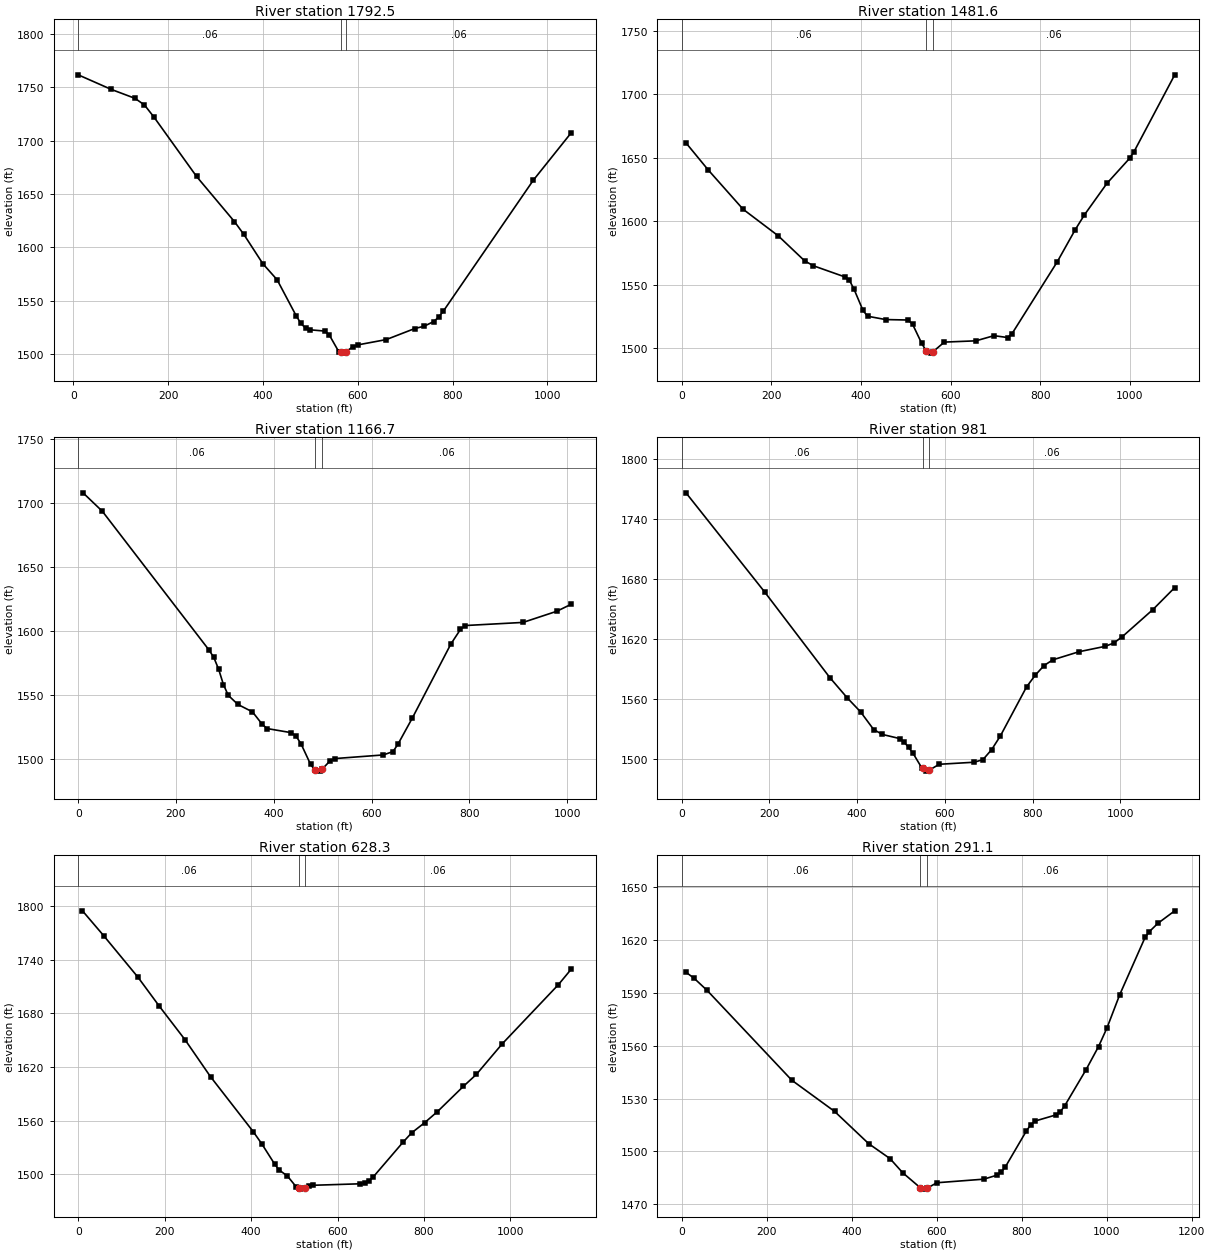
Type RM Length L Ch R = 1 ,1792.5  ,305.8,310.8,315.9
XS GIS Cut Line= 4
     1820376.785      158440.383        1820018.      158242.549
     1819746.397      158172.133     1819397.672      158081.599
#Sta/Elev= 30
      10 1761.59    79.9 1747.92   129.9 1739.58   149.9 1733.33   169.9 1722.04
   259.8 1666.43   339.8 1624.15   359.7 1612.12   399.7 1584.74   429.8 1569.72
   469.8 1536.22   479.9 1528.88   489.9  1524.4   499.9 1522.85     530  1521.7
     540 1517.95     560 1502.33     565 1501.68     570 1501.04     575 1502.41
   590.1 1507.15   600.1 1508.75   660.2 1513.73   720.3 1524.07   740.3 1526.25
   760.4 1530.65   770.4 1534.61   780.4 1540.21   970.5 1662.94  1050.6 1707.39
#Mann= 3 , 0 , 0
      10     .06       0     565    .045       0     575     .06       0
Bank Sta=565,575
XS Rating Curve= 0 ,0
Exp/Cntr=0.3,0.1

Type RM Length L Ch R = 1 ,1481.6  ,307,314.9,322.8
XS GIS Cut Line= 4
     1820440.725      158266.028     1820236.054      158055.169
     1819794.844      157811.885     1819546.881      157638.711
#Sta/Elev= 30
     9.8 1661.57    58.8 1640.51   137.1 1609.36   215.5 1588.43   274.3 1568.75
   293.9 1564.85   364.4 1556.05   374.5 1553.28   384.5 1546.48   404.7 1529.62
   414.8 1525.12   455.1 1522.48   505.5 1522.12   515.5 1518.61   535.7 1503.68
   545.11498.105   555.9 1496.05   560.11496.949   586.1 1504.73   656.6 1505.74
   696.9  1509.8   727.2 1508.33   737.2 1511.42     838 1567.94   878.3 1593.35
   898.5 1604.85   948.9 1629.75   999.3 1649.38  1009.4 1654.76  1100.1 1715.21
#Mann= 3 , 0 , 0
       0     .06       0   545.1    .045       0   560.1     .06       0
Bank Sta=545.1,560.1
XS Rating Curve= 0 ,0
Exp/Cntr=0.3,0.1

Type RM Length L Ch R = 1 ,1166.7  ,184.7,185.7,186.7
XS GIS Cut Line= 4
     1820561.207      158041.361     1820272.838      157769.758
     1820111.888       157568.57     1819806.753      157387.501
#Sta/Elev= 30
     9.9 1708.16    49.5 1693.68   267.4 1585.24   277.3  1579.4   287.2 1570.19
   297.1 1558.11     307 1549.66   326.8 1542.52   356.5 1536.74   376.3 1527.08
   386.2  1523.7   435.8 1520.47   445.7 1517.69   455.6 1511.88   475.4 1495.62
   483.61491.479   495.2 1490.37   498.61491.757   515.1 1498.36     525  1500.2
   624.1 1503.04   643.9 1505.68   653.8 1511.26   683.4 1531.85   762.2 1589.77
   781.9 1601.26   791.8 1604.31     910 1606.75     979 1615.48  1008.6 1620.98
#Mann= 3 , 0 , 0
       0     .06       0   483.6    .045       0   498.6     .06       0
Bank Sta=483.6,498.6
XS Rating Curve= 0 ,0
Exp/Cntr=0.3,0.1

Type RM Length L Ch R = 1 ,981     ,359.7,352.8,345.8
XS GIS Cut Line= 4
     1820754.687      157972.312     1820508.202      157787.144
     1820211.313      157374.798     1819951.535       157209.86
#Sta/Elev= 30
     9.9 1766.52     189 1667.32   338.2  1581.2     378 1560.87   407.9 1547.08
   437.8 1529.33   457.7 1524.43   497.6 1520.26   507.5  1516.6   517.5 1511.45
   527.5 1505.58   547.4 1490.96   549.31490.337   557.4 1487.68   564.31488.592
   587.2 1494.54     667  1496.6   686.9  1499.2   706.8 1509.25   726.7 1522.98
   786.5 1572.21   806.4 1583.93   826.3 1593.49   846.2 1599.19   905.7 1607.29
   965.3 1612.68   985.1 1615.99    1005 1622.53  1074.5 1649.61  1124.1 1671.57
#Mann= 3 , 0 , 0
       0     .06       0   549.3    .045       0   564.3     .06       0
Bank Sta=549.3,564.3
XS Rating Curve= 0 ,0
Exp/Cntr=0.3,0.1

Type RM Length L Ch R = 1 ,628.3   ,337.2,337.2,337.1
XS GIS Cut Line= 4
     1820983.701      157709.402     1820735.569      157427.739
     1820417.022      157209.786     1820078.356      157038.776
#Sta/Elev= 30
     9.9 1794.95    59.3 1766.91   138.3 1720.54   187.7 1688.05     247  1650.6
   306.2 1609.02   405.1 1547.39   424.9 1533.72   454.5 1511.13   464.4 1504.74
   484.2 1497.67     504 1485.88   510.11484.164   513.9  1483.1   525.11484.304
   533.7 1486.38   543.6 1487.42   652.5 1489.08   662.4 1489.76   672.3 1492.04
   682.2 1496.56   751.4 1535.64   771.3 1546.11   801.3 1557.47   831.2    1570
   891.1 1598.26   921.1 1611.63     981 1645.92  1110.8 1712.15  1140.7 1729.64
#Mann= 3 , 0 , 0
       0     .06       0   510.1    .045       0   525.1     .06       0
Bank Sta=510.1,525.1
XS Rating Curve= 0 ,0
Exp/Cntr=0.3,0.1

Type RM Length L Ch R = 1 ,291.1   ,195.4,193.6,191.9
XS GIS Cut Line= 4
     1821256.244      157419.478     1821065.397      157243.928
      1820584.12      156916.416     1820287.231      156800.959
#Sta/Elev= 30
      10 1601.85    29.9 1598.25    59.8 1591.51   259.3 1540.43   359.7 1522.77
     440 1504.43   490.2 1495.94   520.3 1487.86   561.41479.402   570.5  1478.6
   576.41478.999   600.6 1482.23     711 1484.26   741.1 1486.48   751.1  1488.2
   761.2 1491.07   811.3 1511.75   821.4 1515.15   831.4 1517.27   881.3  1520.8
   891.2 1522.62   901.2 1525.94     951 1546.26   980.8 1559.58  1000.7 1570.19
  1030.6 1589.03  1090.3 1621.58  1100.3 1624.85  1120.2 1629.54    1160 1636.68
#Mann= 3 , 0 , 0
       0     .06       0   561.4    .045       0   576.4     .06       0
Bank Sta=561.4,576.4
XS Rating Curve= 0 ,0
Exp/Cntr=0.3,0.1

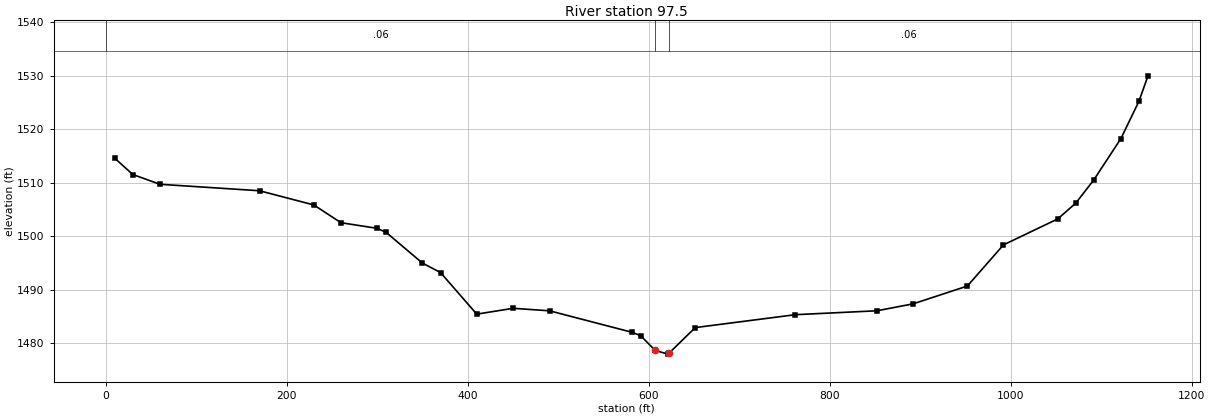
Type RM Length L Ch R = 1 ,97.5    ,89.8,97.5,105
XS GIS Cut Line= 4
     1821359.786      157320.882     1821092.959      157009.536
     1820752.375      156814.647     1820431.614      156676.453
#Sta/Elev= 30
      10 1514.57      30 1511.52      60  1509.7     170 1508.49     230 1505.84
     260 1502.52     300 1501.47     310  1500.7     350 1494.98     370 1493.21
     410 1485.44   450.3 1486.53   490.5 1486.06   581.1 1482.07   591.1 1481.43
   607.11478.664   621.3 1477.97   622.11478.093   651.5 1482.93   762.2 1485.34
   852.3 1486.07   892.3 1487.37   952.1 1490.69     992 1498.38  1051.9 1503.22
  1071.9 1506.18  1091.8 1510.51  1121.8 1518.25  1141.7 1525.21  1151.7 1529.96
#Mann= 3 , 0 , 0
       0     .06       0   607.1    .045       0   622.1     .06       0
Bank Sta=607.1,622.1
XS Rating Curve= 0 ,0
Exp/Cntr=0.3,0.1

Chan Stop Cuts=-1
Use User Specified Reach Order=0